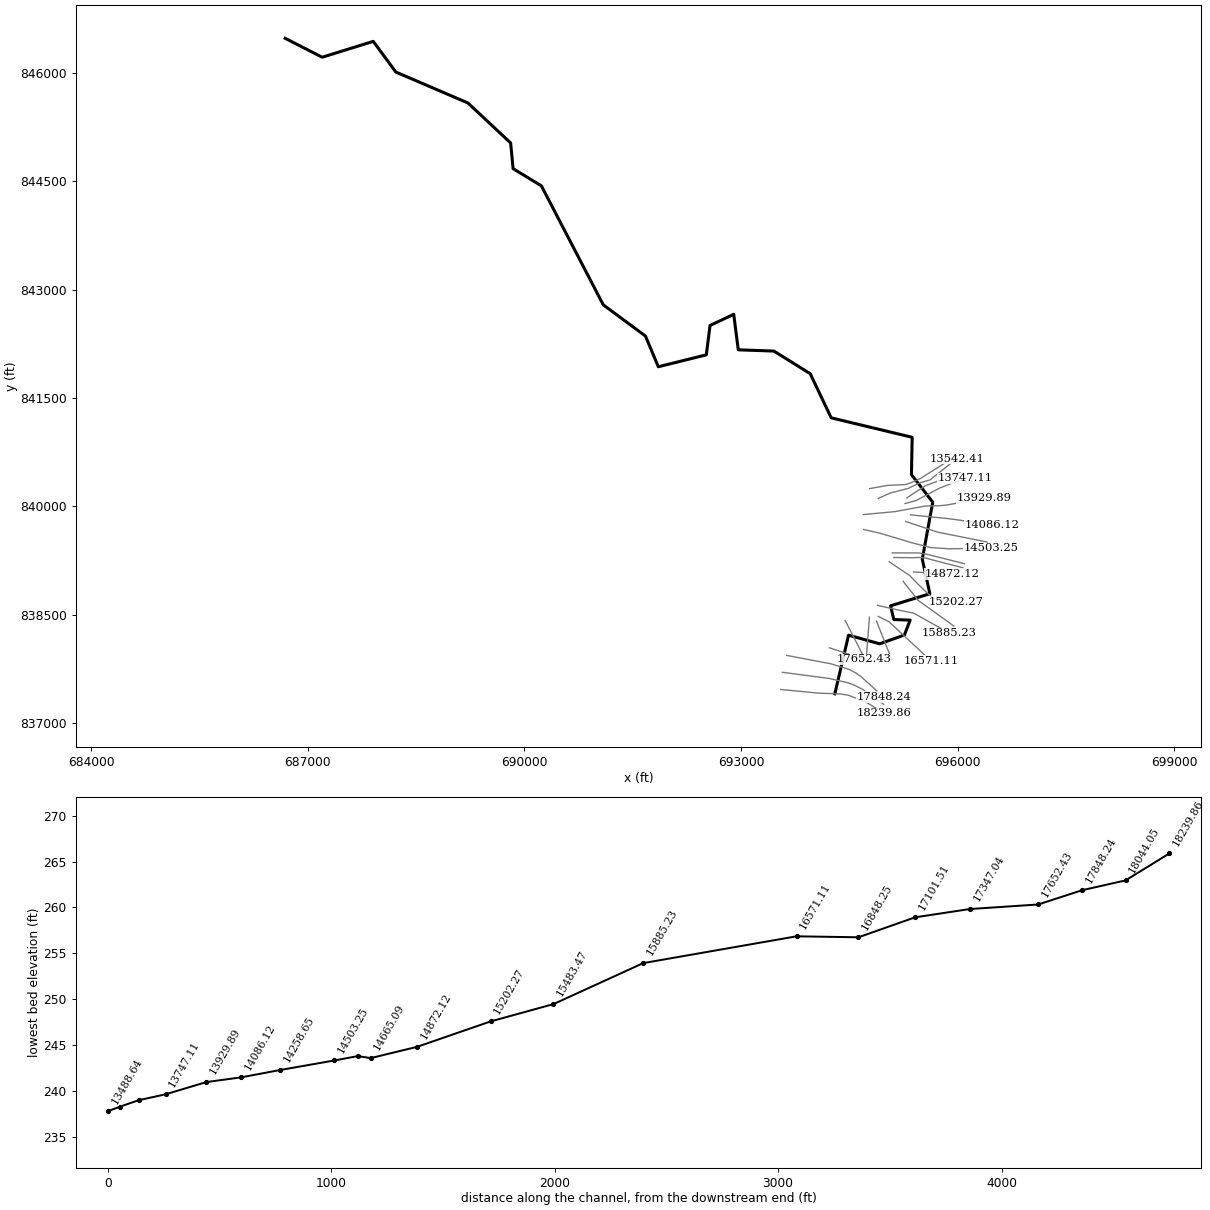
--- 13347_ras.prj (project) ---

Proj Title=13347
Current Plan=p01
Default Exp/Contr=0.3,0.1
English Units
Geom File=g01
Flow File=f01
Plan File=p01
Y Axis Title=Elevation
X Axis Title(PF)=Main Channel Distance
X Axis Title(XS)=Station
BEGIN DESCRIPTION:
RFD model 13347 exported to HEC-RAS
END DESCRIPTION:

--- 13347_ras.p01 (plan) ---

Plan Title=Plan 01
Program Version=4.10
Short Identifier=Plan 01
Geom File=g01
Flow File=f01
Subcritical Flow
Calc Critical at every XS
Secant Critical Depth

--- 13347_ras.f01 (steady flow) ---

Flow Title=Flow 01
Program Version=5.01
Number of Profiles= 6
Profile Names=10yr,25yr,50yr,100yr,100plus,500yr
River Rch & RM=13347,60,18239.86
11469.6913533.1214705.5615596.2219540.1716817.56
River Rch & RM=13347,60,18044.05
11483.8513559.9114742.8515644.3519600.4616890.52
River Rch & RM=13347,60,17848.24
11486.0913564.1614748.7715651.9919610.0416902.11
River Rch & RM=13347,60,17652.43
11486.8913565.6814750.8815654.7219613.4516906.25
River Rch & RM=13347,60,17347.04
11500.3213591.1214786.3215700.4819670.7816975.72
River Rch & RM=13347,60,17101.51
11504.3113598.6714796.8415714.0719687.8116996.38
River Rch & RM=13347,60,16848.25
11508.4413606.5114807.7715728.1919705.5117017.84
River Rch & RM=13347,60,16571.11
11509.8813609.2314811.5515733.0719711.6317025.27
River Rch & RM=13347,60,15885.23
11534.8813656.6614877.6915818.5819818.7617155.41
River Rch & RM=13347,60,15483.47
11541.3313668.9114894.7815840.6919846.4517189.11
River Rch & RM=13347,60,15202.27
11550.27 13685.914918.4915871.3719884.89 17235.9
River Rch & RM=13347,60,14872.12
 11550.913687.0914920.1615873.5219887.5917239.19
River Rch & RM=13347,60,14665.09
11554.6513694.2314930.1215886.4219903.7517258.87
River Rch & RM=13347,60,14607.77
11555.1213695.1214931.3715888.0319905.7717261.33
River Rch & RM=13347,60,14503.25
11556.5313697.79 14935.115892.8619911.8217268.71
River Rch & RM=13347,60,14258.65
11557.7813700.1714938.4215897.1619917.2117275.27
River Rch & RM=13347,60,14086.12
11558.8713702.2514941.3215900.9219921.91   17281
River Rch & RM=13347,60,13929.89
11559.1813702.8414942.1515901.9919923.2617282.64
River Rch & RM=13347,60,13747.11
12985.14 16512.918973.9521264.3726641.6725996.93
River Rch & RM=13347,60,13626.67
12985.5216513.6918975.1121265.9526643.6425999.64
River Rch & RM=13347,60,13542.41
   1298916520.7718985.5321280.1626661.4526024.05
River Rch & RM=13347,60,13488.64
12990.92 16524.718991.3121288.0526671.3326037.61
River Rch & RM=13347,60,13078.58
12993.52   1653018999.1221298.6926684.67 26055.9
River Rch & RM=13347,60, 12761.5
13002.8516549.0319027.1321336.8926732.5326121.59
River Rch & RM=13347,60,12688.69
13003.1416549.6219027.9921338.07   2673426123.62
River Rch & RM=13347,60,12472.62
13024.2716592.7819091.5621424.83 26842.726272.96
River Rch & RM=13347,60,12255.68
13061.4216668.7319203.55 21577.827034.3626536.91
River Rch & RM=13347,60,12130.97
 13061.8 16669.519204.6921579.3627036.31 26539.6
River Rch & RM=13347,60,11818.11
13127.0616803.2619402.25 21849.727375.0127007.92
River Rch & RM=13347,60,11577.41
 13128.916807.0519407.8521857.3727384.6227021.24
River Rch & RM=13347,60,11336.72
13135.3516820.2919427.44 21884.227418.2427067.86
River Rch & RM=13347,60,11096.02
 13141.616833.1319446.4321910.2327450.85 27113.1
River Rch & RM=13347,60,10855.33
13142.9816835.9619450.6221915.9727458.0427123.08
River Rch & RM=13347,60,10614.64
13146.8316843.8819462.3321932.0227478.15   27151
River Rch & RM=13347,60,10373.94
13148.7616847.8319468.1821940.0527488.2127164.96
River Rch & RM=13347,60,10133.25
13156.2716863.2619491.0121971.3527527.4227219.42
River Rch & RM=13347,60,9892.556
13157.0916864.9519493.5221974.7827531.73 27225.4
River Rch & RM=13347,60,9508.713
 13160.216871.3319502.9721987.7427547.9627247.97
River Rch & RM=13347,60,9162.862
 13175.516902.8119549.5722051.6827628.0727359.35
River Rch & RM=13347,60, 8868.58
13180.6816913.4619565.3522073.3227655.1927397.09
River Rch & RM=13347,60,8763.008
13181.1316914.3919566.7322075.2227657.56 27400.4
River Rch & RM=13347,60, 8541.27
13182.0416916.2619569.4922079.0227662.3227407.02
River Rch & RM=13347,60,8319.531
13198.8616950.8919620.8222149.48 27750.627529.99
River Rch & RM=13347,60,8199.644
13199.3116951.82 19622.222151.3727752.9727533.29
River Rch & RM=13347,60,7954.729
13214.7916983.7119669.4822216.3227834.3427646.77
River Rch & RM=13347,60,7709.814
13217.1216988.5219676.6122226.1127846.61 27663.9
River Rch & RM=13347,60,7464.898
13220.4416995.3619686.7522240.0527864.0727688.28
River Rch & RM=13347,60,7219.983
13226.5317007.9119705.3722265.6427896.1427733.06
River Rch & RM=13347,60,6975.068
13237.1517029.8219737.8922310.3527952.1627811.33
River Rch & RM=13347,60,6730.153
13238.4917032.5819741.9922315.9827959.2127821.19
River Rch & RM=13347,60,6485.237
 13240.917037.5419749.3522326.11 27971.927838.93
River Rch & RM=13347,60,6240.322
13243.4817042.8719757.2622336.9827985.5227857.98
River Rch & RM=13347,60,5995.407
13246.4117048.9319766.2522349.3528001.0227879.65
River Rch & RM=13347,60,5750.492
13247.4817051.1319769.5222353.8528006.6527887.53
River Rch & RM=13347,60,5505.576
13266.79   1709119828.7522435.3428108.7528030.48
River Rch & RM=13347,60,5260.661
13268.0317093.5619832.5422440.5628115.2928039.65
River Rch & RM=13347,60,5015.746
14357.15 19398.823320.4927328.9434239.8436984.94
River Rch & RM=13347,60,4770.831
14359.83 19404.623329.4127341.6634255.7737009.13
River Rch & RM=13347,60,4525.915
14379.8919448.0823396.3827437.1734375.4337190.89
River Rch & RM=13347,60,    4281
14380.4619449.3223398.2827439.8834378.8337196.06
Boundary for River Rch & Prof#=13347,60,1
Up Type= 0
Dn Type= 2
Boundary for River Rch & Prof#=13347,60,2
Up Type= 0
Dn Type= 2
Boundary for River Rch & Prof#=13347,60,2
Up Type= 0
Dn Type= 2
Boundary for River Rch & Prof#=13347,60,2
Up Type= 0
Dn Type= 2
Boundary for River Rch & Prof#=13347,60,2
Up Type= 0
Dn Type= 2
Boundary for River Rch & Prof#=13347,60,2
Up Type= 0
Dn Type= 2

--- 13347_ras.g01 (geometry) ---

Geom Title=13347
Program Version=4.10

River Reach=13347,60
Reach XY= 30
694300.284020084837402.192096069694490.675276686838214.510854339
 694921.79230363838094.830065851695263.992809074838216.778451681
695343.399779178838422.733006196 695117.45422684838431.391039085
695071.931587351838620.991595131695616.602624315838788.542717068
695511.680136549839266.461258409695656.436031427840056.700381711
695361.435431152840438.041841695695371.568936109840955.233811493
694250.060575272841224.963112474693959.528089997 841836.27191301
693456.435162426 842149.54892714692962.837580683842166.922940594
692900.120862629842658.749896286692571.602369309842503.657733104
692520.288194867842097.293795481691855.672363315841932.068198973
691677.461066995842357.755267135691093.121574699842789.709529898
690235.640764597  844438.6169039689844.238255439844676.017211812
689809.921614254845031.973311538689218.903083027845585.617496574
688219.678360907846014.408954395687907.267013463846439.180812093
687200.024793689 846219.48965106686687.402565733846481.215207538

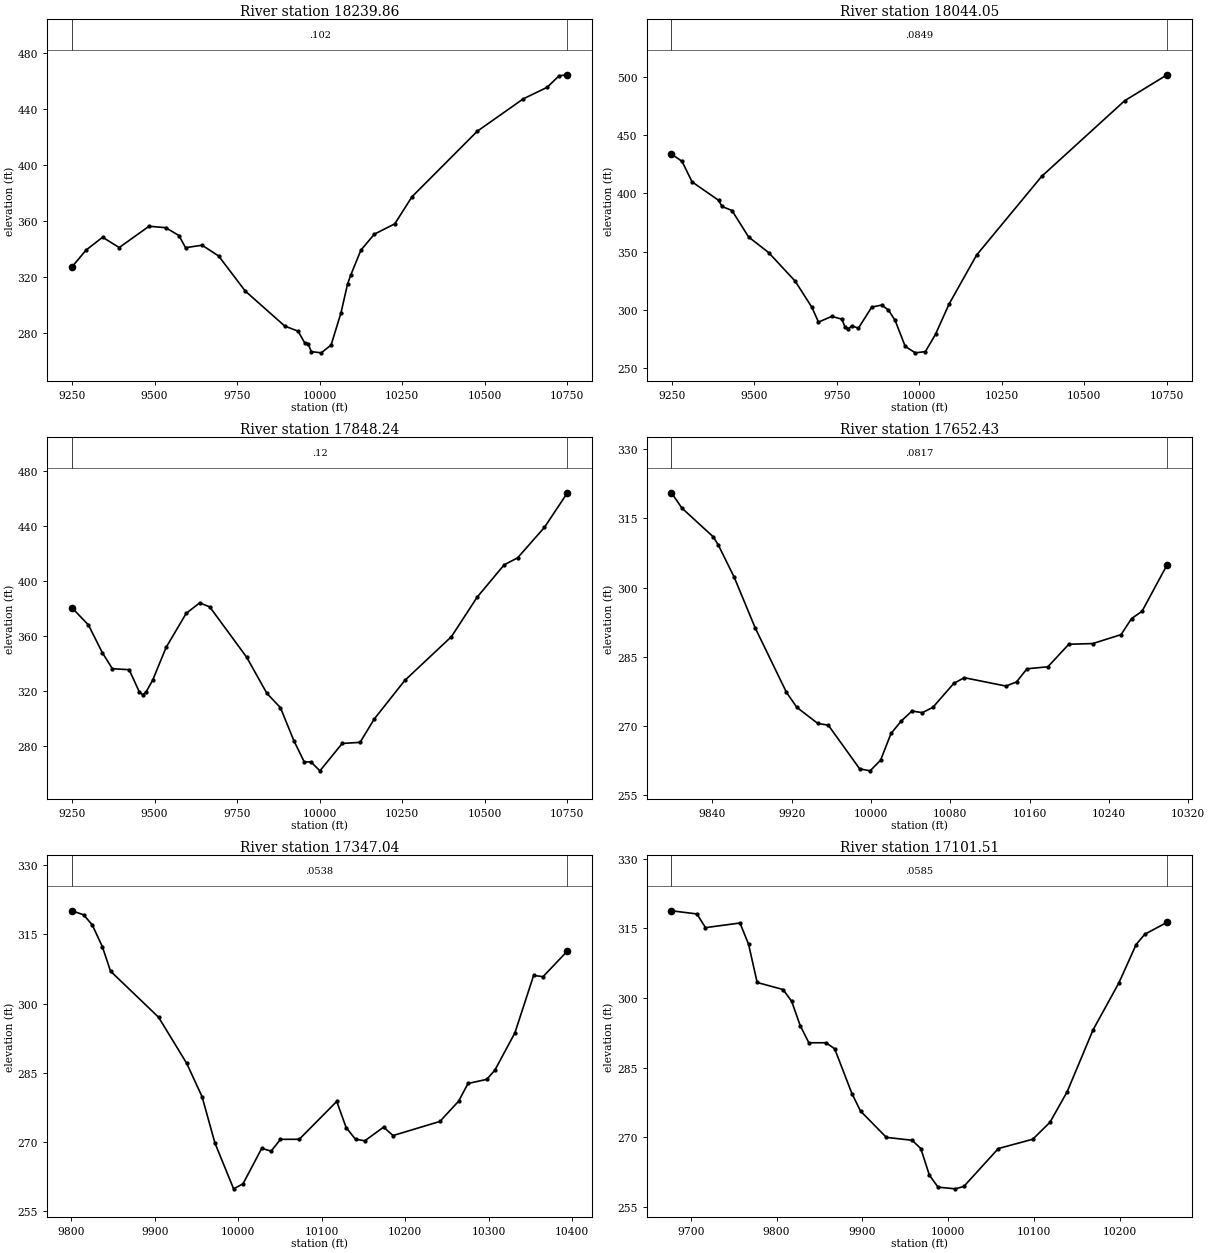
Type RM Length L Ch R = 1 ,18239.86,195.807400,195.807400,195.807400
XS GIS Cut Line= 6
693551.952109236837462.091226603694080.556210586837411.289296152
694372.986488345837401.127684104694485.880056643837383.109157156
694721.779732122837293.807752087694986.611112147837131.283285836
#Sta/Elev= 30
9249.026327.05169292.293339.20269342.547348.40489392.801341.03559483.258356.2462
9533.512355.21779573.715349.6197 9593.81340.94219644.002342.70869694.193334.9976
9774.499310.04559894.711  284.969934.741281.35579954.741273.05039964.742272.5527
9974.742266.781310004.74265.889210034.75271.405810064.79294.418510084.89315.2045
10094.96321.713110125.18339.192710165.91350.600710227.71357.937610280.11377.3269
10477.97 424.09110617.68447.232110689.18455.3434 10725.8 463.63610750.91464.3461
#Mann= 3 , 0 , 0
9249.026   0.102       09249.026   0.102       010750.91   0.102       0
#XS Ineff= 2 , 0
       0                               0
Bank Sta=9249.026,10750.91
Exp/Cntr=0.3,0.1

Type RM Length L Ch R = 1 ,18044.05,195.807500,195.807500,195.807500
XS GIS Cut Line= 6
693573.137174766837700.359547529694214.767256515837616.356151263
694481.770224357837555.171314888694578.461077718837518.791138787
694690.825768257837460.774966651694975.909036066837256.696365795
#Sta/Elev= 30
9249.007433.8483 9281.13427.57639311.374409.93619392.026394.05589402.108388.7951
9432.352385.3244 9482.76362.56319543.249349.22289623.901324.57699674.308302.1886
9694.471289.38849734.797294.29379765.042291.92889775.142 285.0939785.243283.8156
9795.345286.09659815.548284.18349855.953302.32269886.258304.03029906.512299.7124
9926.817290.76889957.274268.54089987.833262.952510018.48264.013610049.27279.0035
10090.48305.0588 10173.7347.054610370.72414.663410622.33479.712310750.95502.0263
#Mann= 3 , 0 , 0
9249.007  0.0849       09249.007  0.0849       010750.95  0.0849       0
#XS Ineff= 2 , 0
       09896.751                       0
Bank Sta=9249.007,10750.95
Exp/Cntr=0.3,0.1

Type RM Length L Ch R = 1 ,17848.24,195.807500,195.807500,195.807500
XS GIS Cut Line= 6
693634.010003107837934.237529511694250.158785263837817.119421963
694490.646638808837742.996230057694578.238306418837698.912457753
694664.191700412837639.470764437694975.782456371  837357.8387429
#Sta/Elev= 30
9249.018380.80079299.563368.11119341.567347.97839372.081336.25369422.937335.5406
9453.451319.51149463.622317.31869473.794319.12669494.136327.87929534.822351.7308
9595.849376.58589636.535 384.1869667.048   381.39779.176344.55979840.359318.2745
9881.187307.94279922.306283.69059953.288268.46359974.067268.2852   10001 261.873
10068.54281.818210122.65282.613410165.92299.721510258.07327.693510399.63359.6445
10477.54388.403810559.24411.896110600.09 417.00710681.44439.232310750.93464.3863
#Mann= 3 , 0 , 0
9249.018    0.12       09249.018    0.12       010750.93    0.12       0
#XS Ineff= 2 , 0
       0                               0
Bank Sta=9249.018,10750.93
Exp/Cntr=0.3,0.1

Type RM Length L Ch R = 1 ,17652.43,305.393700,305.393700,305.393700
XS GIS Cut Line= 2
694225.058476031838040.023130149694699.016809404837881.168963492
#Sta/Elev= 30
9798.787320.56319809.272317.25539840.912311.02239846.061309.23429862.006302.2919
9883.099291.3504 9914.74277.33239925.286274.0635 9946.38270.59039956.926270.2203
9988.567260.76119999.113260.323910009.66262.627310020.21268.416810030.75271.1653
 10041.3273.275610051.85 272.92910062.39274.074710083.49279.256110094.03 280.505
10136.22278.683710146.77279.586310157.31282.428310178.41282.8665 10199.5287.7461
10223.67287.895610252.23 289.83510262.78293.314710273.33294.881710298.66304.9706
#Mann= 3 , 0 , 0
9798.787  0.0817       09798.787  0.0817       010298.66  0.0817       0
#XS Ineff= 2 , 0
       0                               0
Bank Sta=9798.787,10298.66
Exp/Cntr=0.3,0.1

Type RM Length L Ch R = 1 ,17347.04,245.526400,245.526400,245.526400
XS GIS Cut Line= 2
694443.808476031838417.627296805694714.641809404837888.981463492
#Sta/Elev= 30
9800.316320.09779814.504319.22959824.861317.04029836.976312.31749846.793307.0035
9904.391297.01719938.099287.01839956.451279.81379971.807 269.7989994.279259.8298
10005.52260.917210027.99268.612310039.22267.999410050.46  270.5610072.93 270.572
10117.87278.778910129.11273.116710140.35270.567410151.58 270.24910174.05273.2104
10185.29271.376410241.47274.433410263.94 278.83410275.18 282.66410297.65283.5576
10307.36285.549410331.36293.624810353.83306.097310365.07305.8125 10394.3 311.377
#Mann= 3 , 0 , 0
9800.316  0.0538       09800.316  0.0538       0 10394.3  0.0538       0
#XS Ineff= 2 , 0
       0                               0
Bank Sta=9800.316,10394.3
Exp/Cntr=0.3,0.1

Type RM Length L Ch R = 1 ,17101.51,253.262200,253.262200,253.262200
XS GIS Cut Line= 2
694779.745976031838464.502296805694735.475142747837888.981463492
#Sta/Elev= 30
9677.587318.76659707.177318.08729717.206315.13559757.325316.13539767.354311.5757
9777.384303.33289807.472301.81899817.502299.30769827.531294.04489837.561290.3623
 9857.62290.3608 9867.65289.06299887.709279.43829897.738275.65989927.827270.0014
9957.915269.37629967.945267.58719977.975261.85699988.004259.291610008.06258.9242
10018.09259.441510058.21267.592510098.33269.601810118.39273.249310138.45279.8412
10168.54293.133210198.62303.236210218.68311.487210228.71313.705610254.81316.2904
#Mann= 3 , 0 , 0
9677.587  0.0585       09677.587  0.0585       010254.81  0.0585       0
#XS Ineff= 2 , 0
       0                               0
Bank Sta=9677.587,10254.81
Exp/Cntr=0.3,0.1

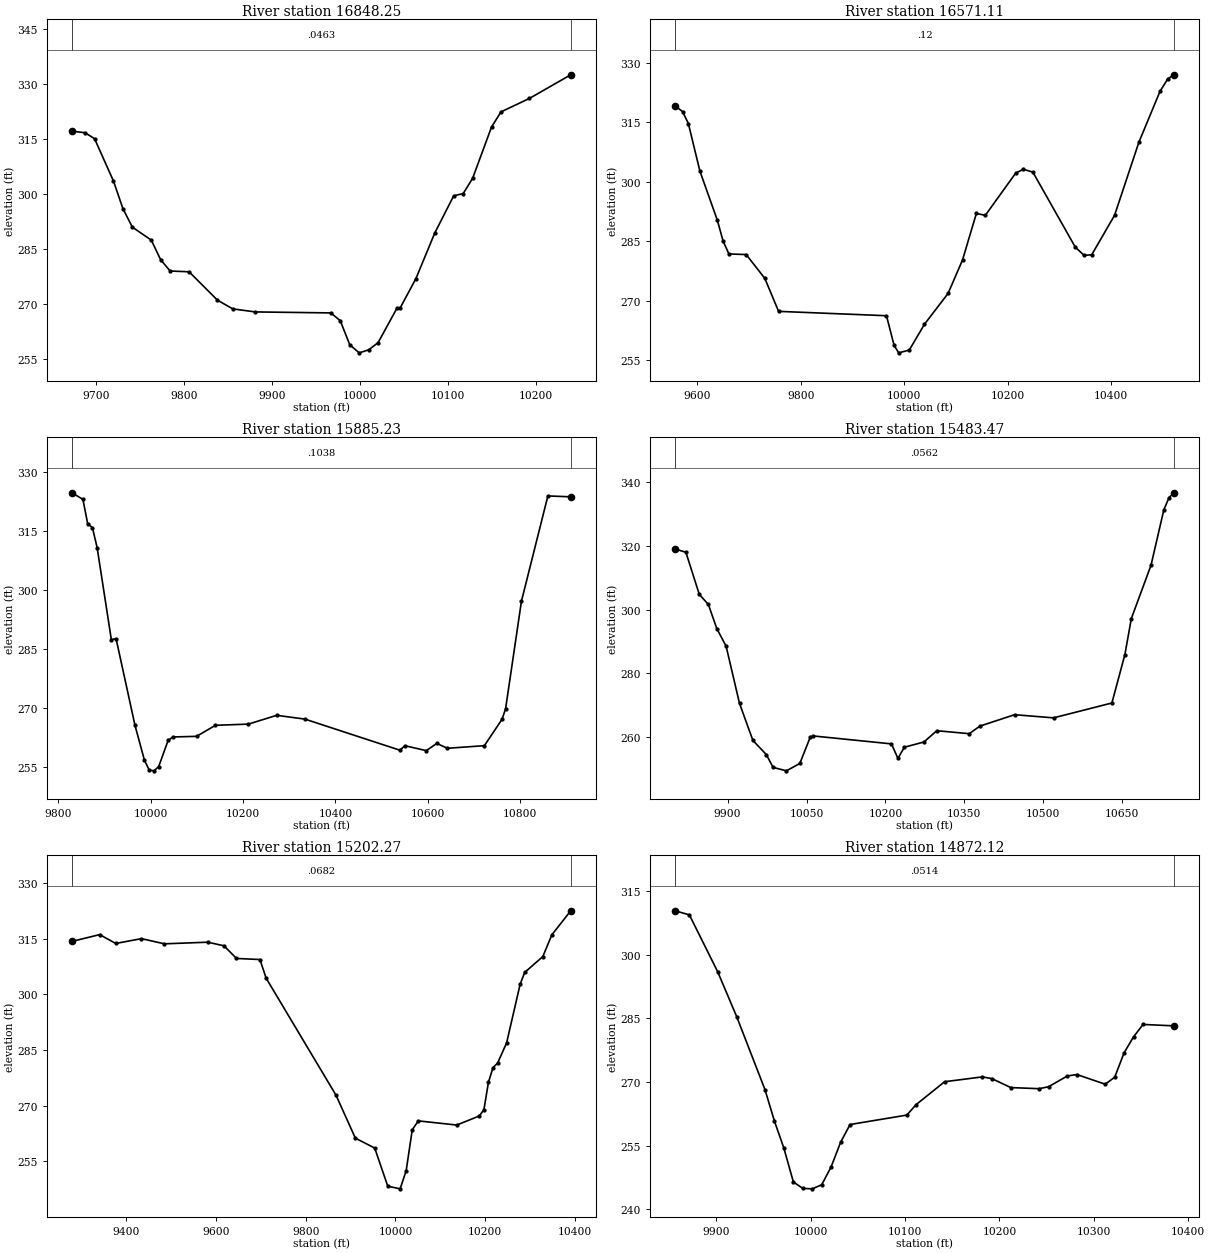
Type RM Length L Ch R = 1 ,16848.25,277.145700,277.145700,277.145700
XS GIS Cut Line= 2
694877.836253822838408.946741268695086.169587165837881.168963492
#Sta/Elev= 30
9672.064317.18099687.058316.74299697.809315.12099719.311303.58649730.062296.0682
9740.813291.00639762.315287.48829773.066282.10319783.816279.05289805.318278.8447
9837.571271.11769854.989268.73679880.575267.90459966.582267.63219977.333265.4953
9988.083258.95789998.834 256.75110009.59257.568110020.34259.532810041.84268.9589
10045.64269.088210063.34276.987910084.84289.442210106.34299.561110117.09300.1497
10127.85304.320210149.35318.3023 10160.1322.429410192.35326.083510239.47332.5428
#Mann= 3 , 0 , 0
9672.064  0.0463       09672.064  0.0463       010239.47  0.0463       0
#XS Ineff= 2 , 0
       0                               0
Bank Sta=9672.064,10239.47
Exp/Cntr=0.3,0.1

Type RM Length L Ch R = 1 ,16571.11,685.877800,685.877800,685.877800
XS GIS Cut Line= 3
694902.141809404838474.918963477695047.975142717838402.002296805
695634.780698299 837856.86340794
#Sta/Elev= 30
9557.116 319.1249571.492317.66459582.672314.66389605.033302.63789638.574290.3206
9649.754285.06049660.934281.78959694.475281.62559730.451275.61649757.049267.3121
9965.531266.21389980.224258.75149989.087256.856710009.61257.557610038.99 264.077
10084.63271.847210112.46280.264210139.23291.991710156.53291.5147 10215.3302.1764
   10230303.120210248.42302.409410330.32283.514410347.54281.410610362.23281.5937
10406.31291.528410453.16309.893210494.11322.773110509.16325.924710521.11326.9464
#Mann= 3 , 0 , 0
9557.116    0.12       09557.116    0.12       010521.11    0.12       0
#XS Ineff= 2 , 0
       0                               0
Bank Sta=9557.116,10521.11
Exp/Cntr=0.3,0.1

Type RM Length L Ch R = 1 ,15885.23,401.763300,401.763300,401.763300
XS GIS Cut Line= 4
694891.725142747838627.696741253695183.391809404838561.724519044
695391.725142717838520.057852358695888.252920479838242.280074596
#Sta/Elev= 30
9829.183324.72249853.046323.04239863.299316.84149873.551315.86119883.804310.7535
9914.562 287.3339924.814287.58299965.825 265.499 9986.33256.60749996.583254.1515
10006.84253.939410017.09255.020310037.59261.699310047.85262.561310099.11262.7181
10140.06265.528710211.44 265.83310272.63268.072210333.82267.107710539.22259.2059
10550.68260.328110596.82  259.0810619.43260.919710642.35 259.68310722.56260.3461
10760.68267.050410768.39269.686210802.77297.098810860.06323.919910909.62323.6923
#Mann= 3 , 0 , 0
9829.183  0.1038       09829.183  0.1038       010909.62  0.1038       0
#XS Ineff= 2 , 0
       0                10518.81       0
Bank Sta=9829.183,10909.62
Exp/Cntr=0.3,0.1

Type RM Length L Ch R = 1 ,15483.47,281.200200,281.200200,281.200200
XS GIS Cut Line= 3
695245.891809404838961.030074582695454.225142717838697.141185716
695950.752920538838339.502296805
#Sta/Elev= 30
9800.268318.98119820.692317.97369846.173304.76179863.382301.6134 9879.52294.0261
9897.136288.54069922.618270.59029948.099258.99379973.581 254.5749986.321250.5567
 10011.8249.472310037.28251.790710057.04260.020710062.77260.405110211.38257.9203
10223.71 253.38510236.03256.8832   10273258.501610297.65262.046810359.27261.1181
10379.69263.501510445.54267.066210519.48266.0738 10630.4270.733110655.04285.8714
10667.37297.204110704.78313.918510728.99331.1906   10739335.1214 10748.4336.6097
#Mann= 3 , 0 , 0
9800.268  0.0562       09800.268  0.0562       0 10748.4  0.0562       0
#XS Ineff= 2 , 0
       0                10418.15       0
Bank Sta=9800.268,10748.4
Exp/Cntr=0.3,0.1

Type RM Length L Ch R = 1 ,15202.27,330.149800,330.149800,330.149800
XS GIS Cut Line= 6
695053.181662932839230.379043696695338.580963529839039.344998625
695455.486058533838919.146802366695587.864530772838791.108607933
695659.479114056838726.004441246695976.666614069838680.691941253
#Sta/Elev= 30
9278.498314.26869340.405316.10779376.245313.71799433.597315.0211 9484.74313.6208
9581.377314.05979617.616313.09219645.491309.67819697.752309.39159711.702304.3477
9867.499272.81799910.651261.24379953.802258.57099982.865248.298510010.46247.5865
10023.97252.502710037.49263.5188   10051265.901310136.75264.781610187.26 267.239
10197.36 268.96810207.46276.339310217.57280.258810227.67281.438410247.87286.9082
10278.18302.760810288.28305.917910328.68310.193810348.89316.063410390.98 322.528
#Mann= 3 , 0 , 0
9278.498  0.0682       09278.498  0.0682       010390.98  0.0682       0
#XS Ineff= 2 , 0
       0                10313.33       0
Bank Sta=9278.498,10390.98
Exp/Cntr=0.3,0.1

Type RM Length L Ch R = 1 ,14872.12,207.028700,207.028700,207.028700
XS GIS Cut Line= 3
695389.947864056839089.719719023695695.503419667839072.358607933
695917.725641847839061.941941261
#Sta/Elev= 30
9856.353310.37399871.429309.40399901.478295.9763 9921.51285.44049951.558268.1911
9961.575260.76639971.591254.38249981.607246.43749991.623244.911310001.64244.8096
10011.66  245.7810021.67250.011810031.69255.8049 10041.7  259.98 10101.8 262.198
10111.82264.694310141.86270.066610181.92271.207710191.93270.795310211.95268.6894
10241.99268.4201   10252268.889710272.02271.435610282.03271.752510312.06269.4803
10322.07271.137210332.08276.9191 10342.1280.674210352.11283.569610384.87283.2396
#Mann= 3 , 0 , 0
9856.353  0.0514       09856.353  0.0514       010384.87  0.0514       0
#XS Ineff= 2 , 0
       0                10165.63       0
Bank Sta=9856.353,10384.87
Exp/Cntr=0.3,0.1

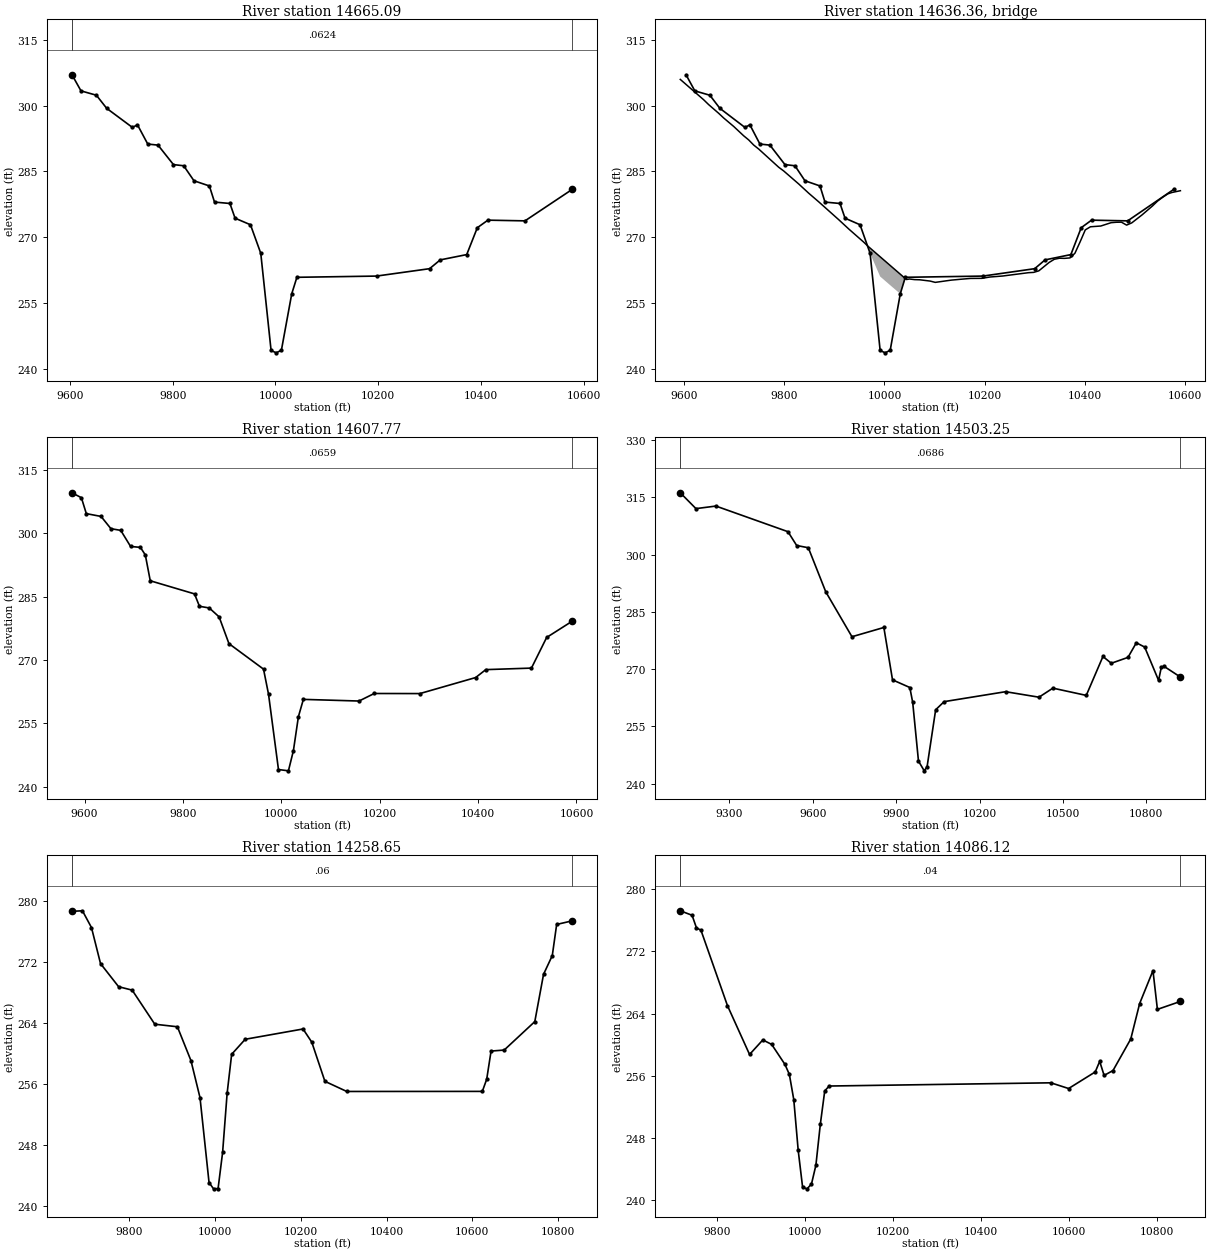
Type RM Length L Ch R = 1 ,14665.09,57.315900,57.315900,57.315900
XS GIS Cut Line= 6
695117.452918828839290.376269877695366.398058563839287.514831513
695476.425751805839290.543116629695557.180022031839282.467689604
695817.612543613839213.826559901696073.975641847839148.747496799
#Sta/Elev= 30
9603.759307.04769621.307303.37229651.309302.3795 9671.31299.39539721.314295.0408
9731.314295.62119751.316291.23929771.317290.99199801.319286.5492 9821.32286.2816
9841.322 282.8579871.329281.67559881.333277.99269911.344277.67449921.348274.3194
 9951.36272.81829971.407266.30699991.506244.126510001.56243.587710011.61244.1882
10031.71257.054310041.76260.827310196.81261.106710300.23262.7959 10320.9264.7996
 10372.5266.010510393.14272.144410413.77273.868810485.98273.708410577.77280.8776
#Mann= 3 , 0 , 0
9603.759  0.0624       09603.759  0.0624       010577.77  0.0624       0
#XS Ineff= 2 , 0
       0                10204.38       0
Bank Sta=9603.759,10577.77
Exp/Cntr=0.3,0.1

Type RM Length L Ch R = 3 ,14636.36,,,
BEGIN DESCRIPTION:
END DESCRIPTION:
Bridge Culvert--1,0,-1,-1, 0
Deck Dist Width WeirC Skew NumUp NumDn MinLoCord MaxHiCord MaxSubmerge Is_Ogee
10.447950,36.420000,2.6,0, 60, 60, , , 0.95, 0, 0,0,,
 9592.24 9638.91 9648.91 9668.91 9678.91 9698.91 9718.91 9728.91 9738.91 9748.91
 9788.91 9798.91 9828.91 9848.91 9868.91 9908.91 9928.91 9958.92 9967.64 9967.64
10039.1610039.1610043.9810050.0110060.2110070.5410091.2510101.6010133.3610153.37
10171.9610194.7810210.5710236.2010287.7910298.1110308.4310329.0710339.3810349.70
10360.0210370.3410371.5510380.6510390.9710401.2910411.6110432.2410452.7610463.20
10473.5110483.8310494.1510514.7910535.4210545.7410556.0610566.3710574.5910591.31
  305.99  301.35  300.24  298.26  297.19  295.26  293.12  292.18  291.01  290.10
  285.94  285.09  282.12  280.01  278.04  273.96  271.84  268.83  267.87  267.87
  260.80  260.80  260.32  260.44  260.30  260.26  259.97  259.67  260.18  260.39
  260.57  260.59  260.89  261.12  261.88  261.95  262.30  264.22  264.94  265.18
  265.15  265.25  265.32  266.33  268.92  271.65  272.36  272.53  273.29  273.39
  273.41  272.74  273.25  275.08  277.10  278.23  279.11  279.88  280.19  280.59
 -694.01 -698.65 -699.76 -701.74 -702.81 -704.74 -706.88 -707.82 -708.99 -709.90
 -714.06 -714.91 -717.88 -719.99 -721.96 -726.04 -728.16 -731.17 -732.13  263.37
  256.30 -739.20 -739.68 -739.56 -739.70 -739.74 -740.03 -740.33 -739.82 -739.61
 -739.43 -739.41 -739.11 -738.88 -738.12 -738.05 -737.70 -735.78 -735.06 -734.82
 -734.85 -734.75 -734.68 -733.67 -731.08 -728.35 -727.64 -727.47 -726.71 -726.61
 -726.59 -727.26 -726.75 -724.92 -722.90 -721.77 -720.89 -720.12 -719.81 -719.41
 9592.24 9638.91 9648.91 9668.91 9678.91 9698.91 9718.91 9728.91 9738.91 9748.91
 9788.91 9798.91 9828.91 9848.91 9868.91 9908.91 9928.91 9958.92 9967.85 9967.85
10039.3710039.3710043.9810050.0110060.2110070.5410091.2510101.6010133.3610153.37
10171.9610194.7810210.5710236.2010287.7910298.1110308.4310329.0710339.3810349.70
10360.0210370.3410371.5510380.6510390.9710401.2910411.6110432.2410452.7610463.20
10473.5110483.8310494.1510514.7910535.4210545.7410556.0610566.3710574.5910591.31
  305.99  301.35  300.24  298.26  297.19  295.26  293.12  292.18  291.01  290.10
  285.94  285.09  282.12  280.01  278.04  273.96  271.84  268.83  267.85  267.85
  260.77  260.77  260.32  260.44  260.30  260.26  259.97  259.67  260.18  260.39
  260.57  260.59  260.89  261.12  261.88  261.95  262.30  264.22  264.94  265.18
  265.15  265.25  265.32  266.33  268.92  271.65  272.36  272.53  273.29  273.39
  273.41  272.74  273.25  275.08  277.10  278.23  279.11  279.88  280.19  280.59
 -694.01 -698.65 -699.76 -701.74 -702.81 -704.74 -706.88 -707.82 -708.99 -709.90
 -714.06 -714.91 -717.88 -719.99 -721.96 -726.04 -728.16 -731.17 -732.15  263.35
  256.27 -739.23 -739.68 -739.56 -739.70 -739.74 -740.03 -740.33 -739.82 -739.61
 -739.43 -739.41 -739.11 -738.88 -738.12 -738.05 -737.70 -735.78 -735.06 -734.82
 -734.85 -734.75 -734.68 -733.67 -731.08 -728.35 -727.64 -727.47 -726.71 -726.61
 -726.59 -727.26 -726.75 -724.92 -722.90 -721.77 -720.89 -720.12 -719.81 -719.41
BR Coef=-1 , 0 , 0 ,, 0 ,,,0.8,0,1,0,
WSPro=,,,, 1 ,,,, 0 ,,,, 0 ,,,,-1 ,-1 ,-1 , 0 , 0 , 0 , 0 , 0
BC Design=,, 0 ,, 0 ,,,,,,

Type RM Length L Ch R = 1 ,14607.77,104.521100,104.521100,104.521100
XS GIS Cut Line= 4
695095.871253222839354.137104452695461.284326106 839353.12767607
695581.406303108839333.948536903696095.205347568839204.741704494
#Sta/Elev= 30
9574.369309.54669593.498308.38049603.498304.61729633.498303.95489653.498301.0583
9673.499300.65939693.499296.85849713.499296.63859723.499294.84259733.499288.7434
9823.499285.64139833.499282.71259853.499282.31289873.499280.20629893.499 273.881
  9963.8267.85179973.927261.9507 9994.18244.121710014.43243.807110024.56248.5814
10034.69256.602710044.81260.701610157.94260.310710188.87 262.09310281.67262.0731
 10395.1265.862810415.72 267.73610508.52 268.09810539.45275.342310591.22279.1744
#Mann= 3 , 0 , 0
9574.369  0.0659       09574.369  0.0659       010591.22  0.0659       0
#XS Ineff= 2 , 0
       0                10190.08       0
Bank Sta=9574.369,10591.22
Exp/Cntr=0.3,0.1

Type RM Length L Ch R = 1 ,14503.25,244.596200,244.596200,244.596200
XS GIS Cut Line= 6
694699.739345006839678.474719225694926.071641255839626.728647035
695363.374504202839495.284782888695629.645409155839427.669478904
 695886.21598118839410.627142623696463.468699034839419.793851115
#Sta/Elev= 30
9123.917316.16849180.272312.01789252.043 312.6899511.128305.97559542.487302.3578
9584.334301.77249647.104290.21989741.259  278.469855.973280.88369887.095267.1658
 9949.34265.16159959.714  261.259980.462245.890310001.19243.332710011.45244.4186
10042.23 259.32710072.76261.459510293.77264.062510413.78262.622510463.78264.9946
10583.79263.094110643.79273.2855 10673.8271.509810733.82273.049610763.83 276.876
10793.84275.754210843.85267.029310853.85270.530310863.85270.687410922.34267.8985
#Mann= 3 , 0 , 0
9123.917  0.0686       09123.917  0.0686       010922.34  0.0686       0
#XS Ineff= 2 , 0
       0                10149.68       0
Bank Sta=9123.917,10922.34
Exp/Cntr=0.3,0.1

Type RM Length L Ch R = 1 ,14258.65,172.535700,172.535700,172.535700
XS GIS Cut Line= 3
695281.874947429839789.372496814695731.093697399 839639.63291347
696410.347169638839505.084302351
#Sta/Elev= 30
9666.559278.64579690.935278.71739712.017276.51479733.098271.79759775.262268.7682
9806.885268.3196 9859.59263.85519912.294  263.529943.917259.08569964.999254.2388
9986.081243.11019996.622242.285310007.16242.3276 10017.7247.053310028.24254.7966
10038.79259.912910070.41261.881710205.22263.229910225.61261.5014 10256.2256.3717
10307.17255.042910623.19255.053310633.39256.643610643.58260.336910674.16260.4686
10745.52264.195710765.91270.3946 10786.3272.847810796.49276.926110832.53277.3966
#Mann= 3 , 0 , 0
9666.559    0.06       09666.559    0.06       010832.53    0.06       0
#XS Ineff= 2 , 0
       0                10076.47       0
Bank Sta=9666.559,10832.53
Exp/Cntr=0.3,0.1

Type RM Length L Ch R = 1 ,14086.12,156.230000,156.230000,156.230000
XS GIS Cut Line= 3
695348.322364956839881.168963492 695869.15569827839829.085630164
696476.794587165839746.620352358
#Sta/Elev= 30
9717.351277.19179744.162276.61489754.212274.98349764.262 274.7099824.561265.0166
 9874.81258.7429 9904.96260.6121 9925.06260.03639955.209 257.4729965.259256.1864
9975.309252.94559985.359246.42849995.409241.679410005.46241.493810015.51242.1087
10025.56244.521610035.61249.772110045.66254.065610055.71254.692810559.52255.1061
10599.89254.372810660.44256.502210670.53257.858910680.62256.054710700.81 256.683
10741.17260.731710761.36265.287510791.63269.504610801.72264.532810853.99265.5556
#Mann= 3 , 0 , 0
9717.351    0.04       09717.351    0.04       010853.99    0.04       0
#XS Ineff= 2 , 0
       0                10105.91       0
Bank Sta=9717.351,10853.99
Exp/Cntr=0.3,0.1

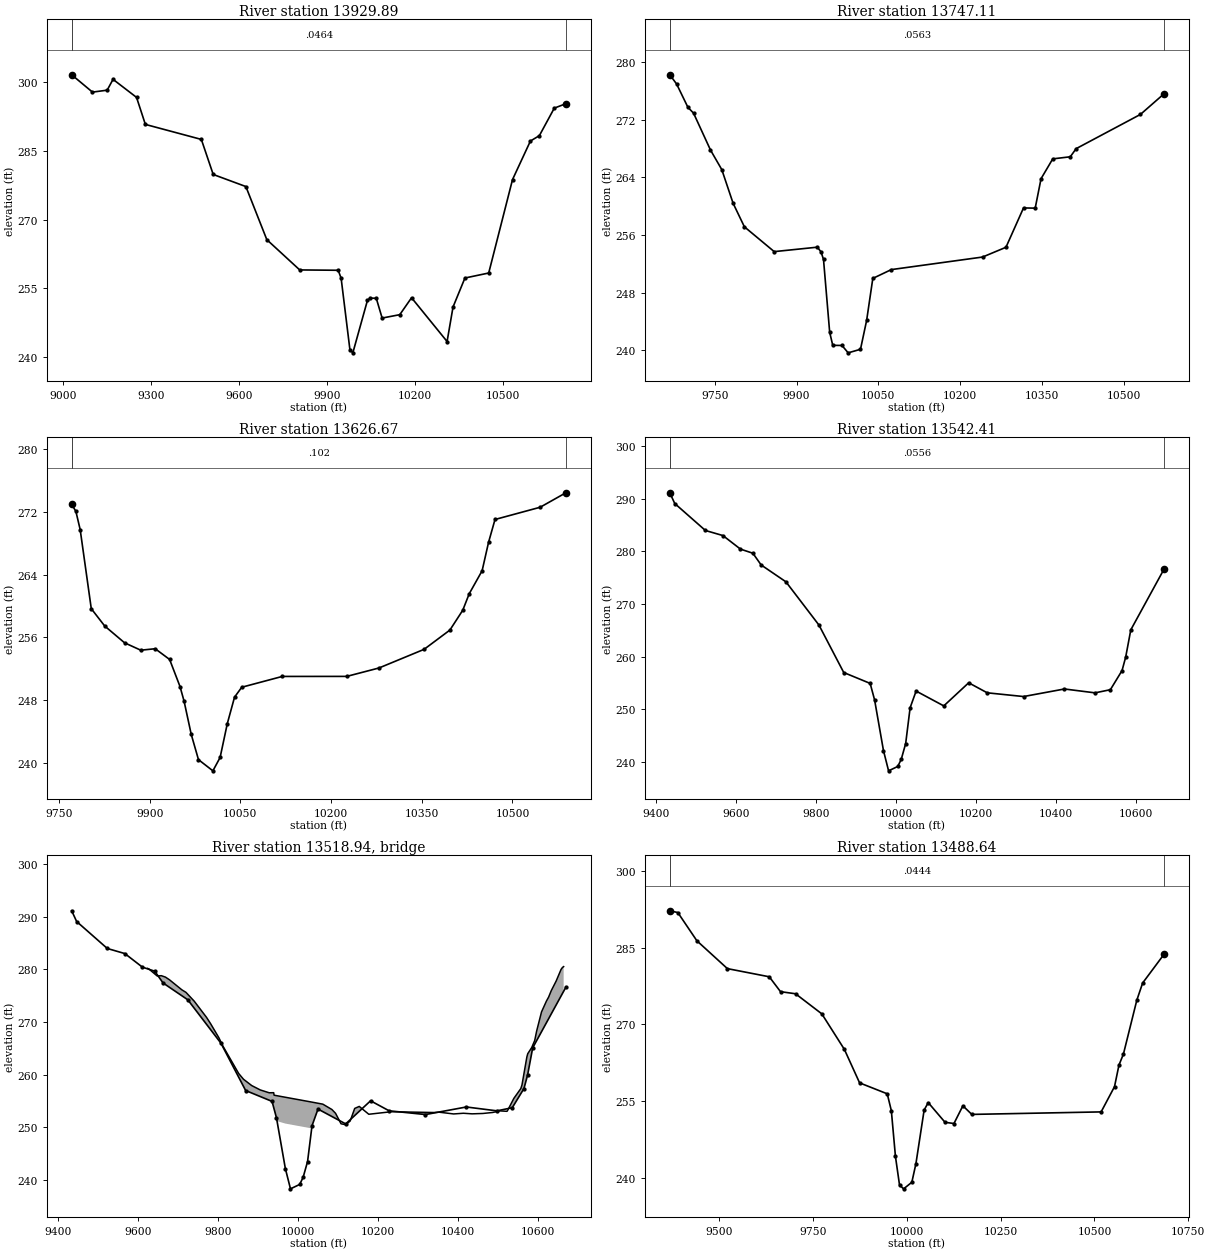
Type RM Length L Ch R = 1 ,13929.89,182.776500,182.776500,182.776500
XS GIS Cut Line= 6
694694.284099489839884.818268806695132.017880857 839925.73942852
695550.974825591840003.057370991695760.434384465840008.291776866
695845.043041468840016.674070865696363.850392431840108.129715338
#Sta/Elev= 30
 9028.07301.50319099.022297.72939149.189298.15079169.256300.50849249.524 296.581
9279.624290.69899470.775287.43239511.268279.80439622.822277.17239694.307265.6144
9806.639259.02429938.032258.94929948.036257.22459978.036241.66769988.036240.9769
10038.04252.427810048.04252.887810068.05 252.85310088.07248.5479 10148.3249.2837
10188.49252.966810309.82243.442410330.12250.955110370.73257.264710451.94258.3521
 10533.2278.684710594.34287.0831 10624.9288.250410675.85294.242410715.43295.2079
#Mann= 3 , 0 , 0
 9028.07  0.0464       0 9028.07  0.0464       010715.43  0.0464       0
#XS Ineff= 2 , 0
       0                10172.87       0
Bank Sta=9028.07,10715.43
Exp/Cntr=0.3,0.1

Type RM Length L Ch R = 1 ,13747.11,120.445900,120.445900,120.445900
XS GIS Cut Line= 4
695272.912801743840037.757401839695424.243873775840078.657691568
695757.581235141840254.528937429696105.233697861840389.499893546
#Sta/Elev= 30
9667.459278.2288 9679.98 276.9479700.698273.71439711.056272.90279742.133267.7845
 9762.85265.06919783.568260.40529804.286257.13359858.994253.6889 9938.14254.3052
 9944.96253.64599949.446252.60299960.753 242.501 9966.39240.68769983.366240.6639
9994.672 239.64310017.29240.135710028.59244.1579 10039.9249.971210073.82251.1933
10241.25252.936510284.16254.293210316.34259.750210337.79259.722410348.52  263.81
10369.97266.558710402.16266.849410412.88267.977210530.88272.729710574.04275.5841
#Mann= 3 , 0 , 0
9667.459  0.0563       09667.459  0.0563       010574.04  0.0563       0
#XS Ineff= 2 , 0
       0                               0
Bank Sta=9667.459,10574.04
Exp/Cntr=0.3,0.1

Type RM Length L Ch R = 1 ,13626.67,84.254100,84.254100,84.254100
XS GIS Cut Line= 3
695299.212044507840117.342839539695559.456186026840286.555079684
696034.964000165840462.193101138
#Sta/Elev= 30
9771.096272.9527    9778272.08519785.143269.74849803.488259.67129825.712  257.46
9858.523255.32099885.352254.37689909.208254.56379933.064253.19589950.248 249.746
 9956.92247.89459968.848 243.6369980.776240.425910004.63238.999810016.56240.7036
10028.49245.027510040.42248.390510052.34249.655510119.41251.033210226.01251.0382
10279.31252.110110353.93254.487810396.58256.9417 10417.9 259.47310428.56 261.574
10449.88 264.50210460.54268.1302 10471.2 271.03910545.82 272.59710588.42 274.443
#Mann= 3 , 0 , 0
9771.096   0.102       09771.096   0.102       010588.42   0.102       0
#XS Ineff= 2 , 0
       0                               0
Bank Sta=9771.096,10588.42
Exp/Cntr=0.3,0.1

Type RM Length L Ch R = 1 ,13542.41,53.772100,53.772100,53.772100
XS GIS Cut Line= 6
694903.710981071840109.478784934 695066.53874281840182.626703545
695322.172757238840249.358474374695481.302364588840326.356671497
695618.359181017840364.735418513695989.983531266840660.321357042
#Sta/Elev= 30
9434.077291.12039446.452 289.0839523.192283.95759567.042282.99169610.893 280.418
9641.995279.63379662.665277.40659724.676274.20449807.357265.98459869.367256.9694
9935.467254.90199946.576251.76239968.795242.13029981.569238.290310004.53239.1236
10013.23240.469910024.34243.480110035.45 250.27310050.45253.446810119.71250.6295
10182.02255.018110228.44253.115410319.37252.405810421.59253.841710498.26253.1075
10536.59253.7066 10565.8257.343810574.92259.9135 10587.7265.078810670.73   276.6
#Mann= 3 , 0 , 0
9434.077  0.0556       09434.077  0.0556       010670.73  0.0556       0
#XS Ineff= 2 , 0
       0                               0
Bank Sta=9434.077,10670.73
Exp/Cntr=0.3,0.1

Type RM Length L Ch R = 3 ,13518.94,,,
BEGIN DESCRIPTION:
END DESCRIPTION:
Bridge Culvert--1,0,-1,-1, 0
Deck Dist Width WeirC Skew NumUp NumDn MinLoCord MaxHiCord MaxSubmerge Is_Ogee
9.661050,34.450000,2.6,0, 60, 60, , , 0.95, 0, 0,0,,
 9624.25 9627.52 9648.09 9658.37 9668.66 9678.94 9709.79 9720.07 9740.64 9771.49
 9781.77 9802.34 9812.62 9851.90 9864.04 9884.60 9906.00 9928.36 9939.54 9940.57
 9947.99 9947.9910032.9610032.9610062.5210085.2610094.3710108.0710119.4810130.88
10142.2910153.7010177.5110233.5410340.9010353.1210389.7910414.2310436.1910463.12
10487.5710505.7610523.1610524.2310540.5510557.9410560.9010573.1210575.3310585.34
10592.7310597.5710609.7910622.0110627.5110634.2310646.4510658.6810662.3010665.13
  280.17  280.05  278.73  278.79  278.52  278.00  276.10  275.62  273.95  270.87
  269.66  267.01  265.40  260.21  259.11  257.91  257.08  256.54  256.56  256.08
  255.98  255.98  254.80  254.80  254.38  253.36  252.64  250.65  250.48  251.17
  253.57  253.95  252.46  252.94  252.79  252.86  252.52  252.65  252.54  252.61
  252.80  253.10  253.02  253.09  255.48  257.34  258.04  263.36  263.97  265.15
  266.48  268.27  271.91  273.96  274.72  275.96  277.78  279.98  280.36  280.51
 -719.83 -719.95 -721.27 -721.21 -721.48 -722.00 -723.90 -724.38 -726.05 -729.13
 -730.34 -732.99 -734.60 -739.79 -740.89 -742.09 -742.92 -743.46 -743.44 -743.92
 -744.02  250.98  249.80 -745.20 -745.62 -746.64 -747.36 -749.35 -749.52 -748.83
 -746.43 -746.05 -747.54 -747.06 -747.21 -747.14 -747.48 -747.35 -747.46 -747.39
 -747.20 -746.90 -746.98 -746.91 -744.52 -742.66 -741.96 -736.64 -736.03 -734.85
 -733.52 -731.73 -728.09 -726.04 -725.28 -724.04 -722.22 -720.02 -719.64 -719.49
 9624.25 9627.52 9648.09 9658.37 9668.66 9678.94 9709.79 9720.07 9740.64 9771.49
 9781.77 9802.34 9812.62 9851.90 9864.04 9884.60 9906.00 9928.36 9939.54 9940.57
 9956.69 9956.6910041.6610041.6610062.5210085.2610094.3710108.0710119.4810130.88
10142.2910153.7010177.5110233.5410340.9010353.1210389.7910414.2310436.1910463.12
10487.5710505.7610523.1610524.2310540.5510557.9410560.9010573.1210575.3310585.34
10592.7310597.5710609.7910622.0110627.5110634.2310646.4510658.6810662.3010665.13
  280.17  280.05  278.73  278.79  278.52  278.00  276.10  275.62  273.95  270.87
  269.66  267.01  265.40  260.21  259.11  257.91  257.08  256.54  256.56  256.08
  255.86  255.86  254.68  254.68  254.38  253.36  252.64  250.65  250.48  251.17
  253.57  253.95  252.46  252.94  252.79  252.86  252.52  252.65  252.54  252.61
  252.80  253.10  253.02  253.09  255.48  257.34  258.04  263.36  263.97  265.15
  266.48  268.27  271.91  273.96  274.72  275.96  277.78  279.98  280.36  280.51
 -719.83 -719.95 -721.27 -721.21 -721.48 -722.00 -723.90 -724.38 -726.05 -729.13
 -730.34 -732.99 -734.60 -739.79 -740.89 -742.09 -742.92 -743.46 -743.44 -743.92
 -744.14  250.86  249.68 -745.32 -745.62 -746.64 -747.36 -749.35 -749.52 -748.83
 -746.43 -746.05 -747.54 -747.06 -747.21 -747.14 -747.48 -747.35 -747.46 -747.39
 -747.20 -746.90 -746.98 -746.91 -744.52 -742.66 -741.96 -736.64 -736.03 -734.85
 -733.52 -731.73 -728.09 -726.04 -725.28 -724.04 -722.22 -720.02 -719.64 -719.49
BR Coef=-1 , 0 , 0 ,, 0 ,,,0.8,0,1,0,
WSPro=,,,, 1 ,,,, 0 ,,,, 0 ,,,,-1 ,-1 ,-1 , 0 , 0 , 0 , 0 , 0
BC Design=,, 0 ,, 0 ,,,,,,

Type RM Length L Ch R = 1 ,13488.64,410.056000,410.056000,410.056000
XS GIS Cut Line= 6
694783.919314414840244.628357574695029.934463246840289.227595104
695270.840625823840299.663963169695338.599039286840319.170173079
695483.355649889840382.822016031695987.979143471840702.293955892
#Sta/Elev= 30
9368.189 292.2269389.613291.88169440.428286.35049521.732280.90359633.293279.3074
9663.321276.39179703.359275.98379773.425272.04649833.481   265.1 9874.08 258.542
9947.772256.40019958.697253.09859969.621244.14699980.545238.52689991.469   237.8
10013.32239.090710024.24242.738910046.09253.220110057.01254.681210101.83250.8216
 10125.6250.587410149.38254.053110173.15252.368310517.86  252.8610553.51257.8021
 10565.4262.028510577.29264.181710612.95274.719110628.48278.087510685.38283.7019
#Mann= 3 , 0 , 0
9368.189  0.0444       09368.189  0.0444       010685.38  0.0444       0
#XS Ineff= 2 , 0
       0                               0
Bank Sta=9368.189,10685.38
Exp/Cntr=0.3,0.1