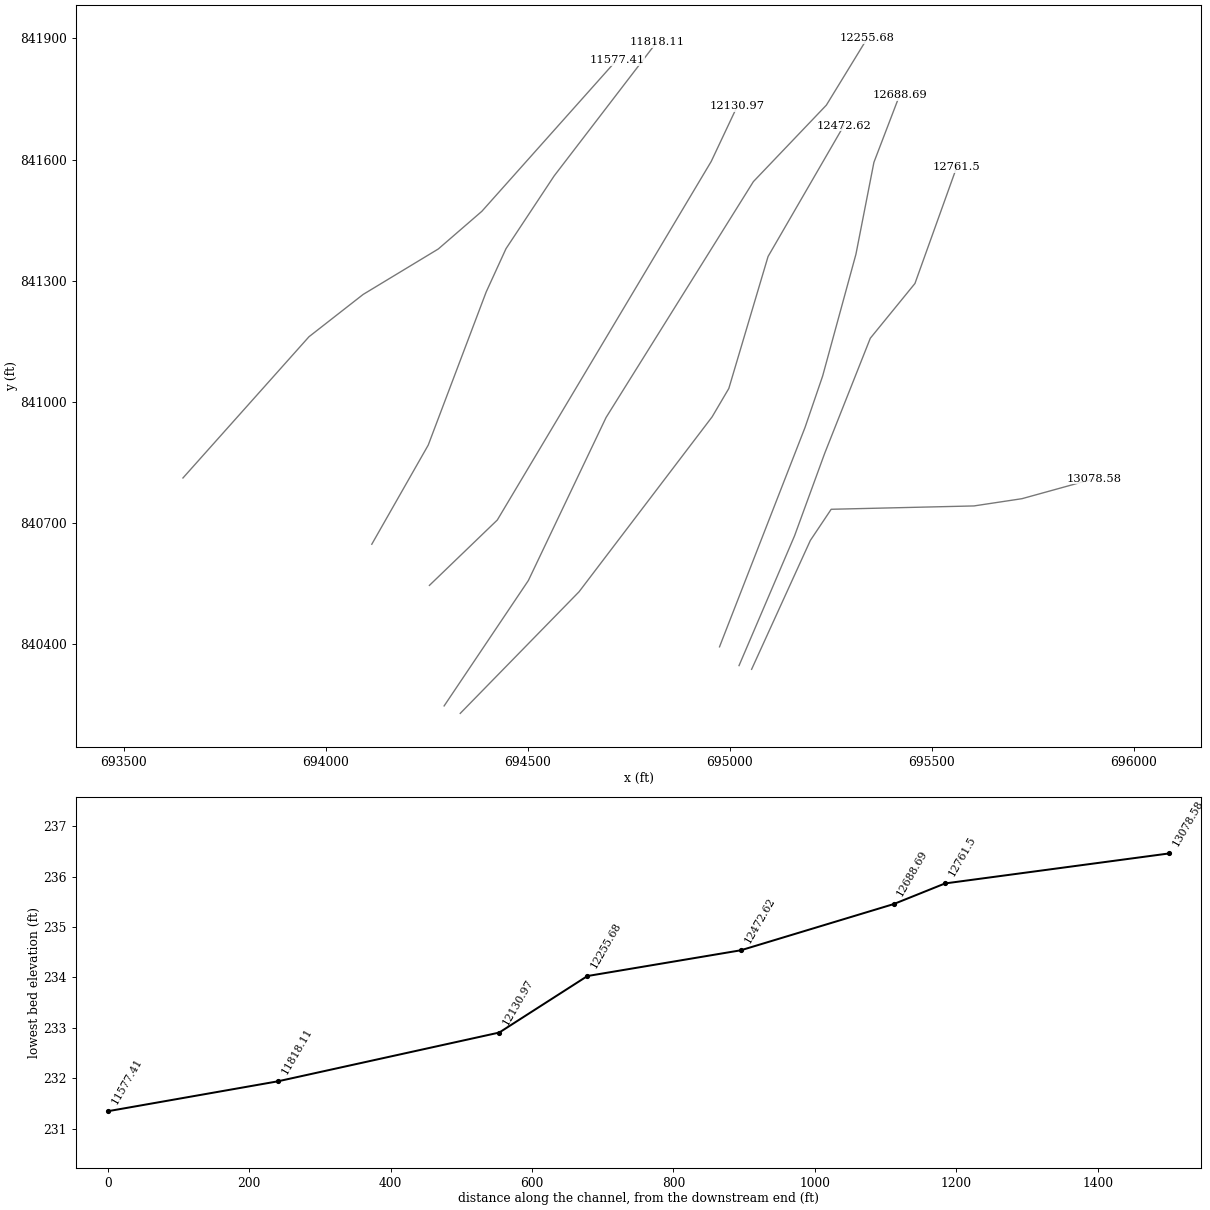
HEC-RAS study 13347_ras.prj: 13347

--- 13347_ras.g01 (geometry) --- (continued)

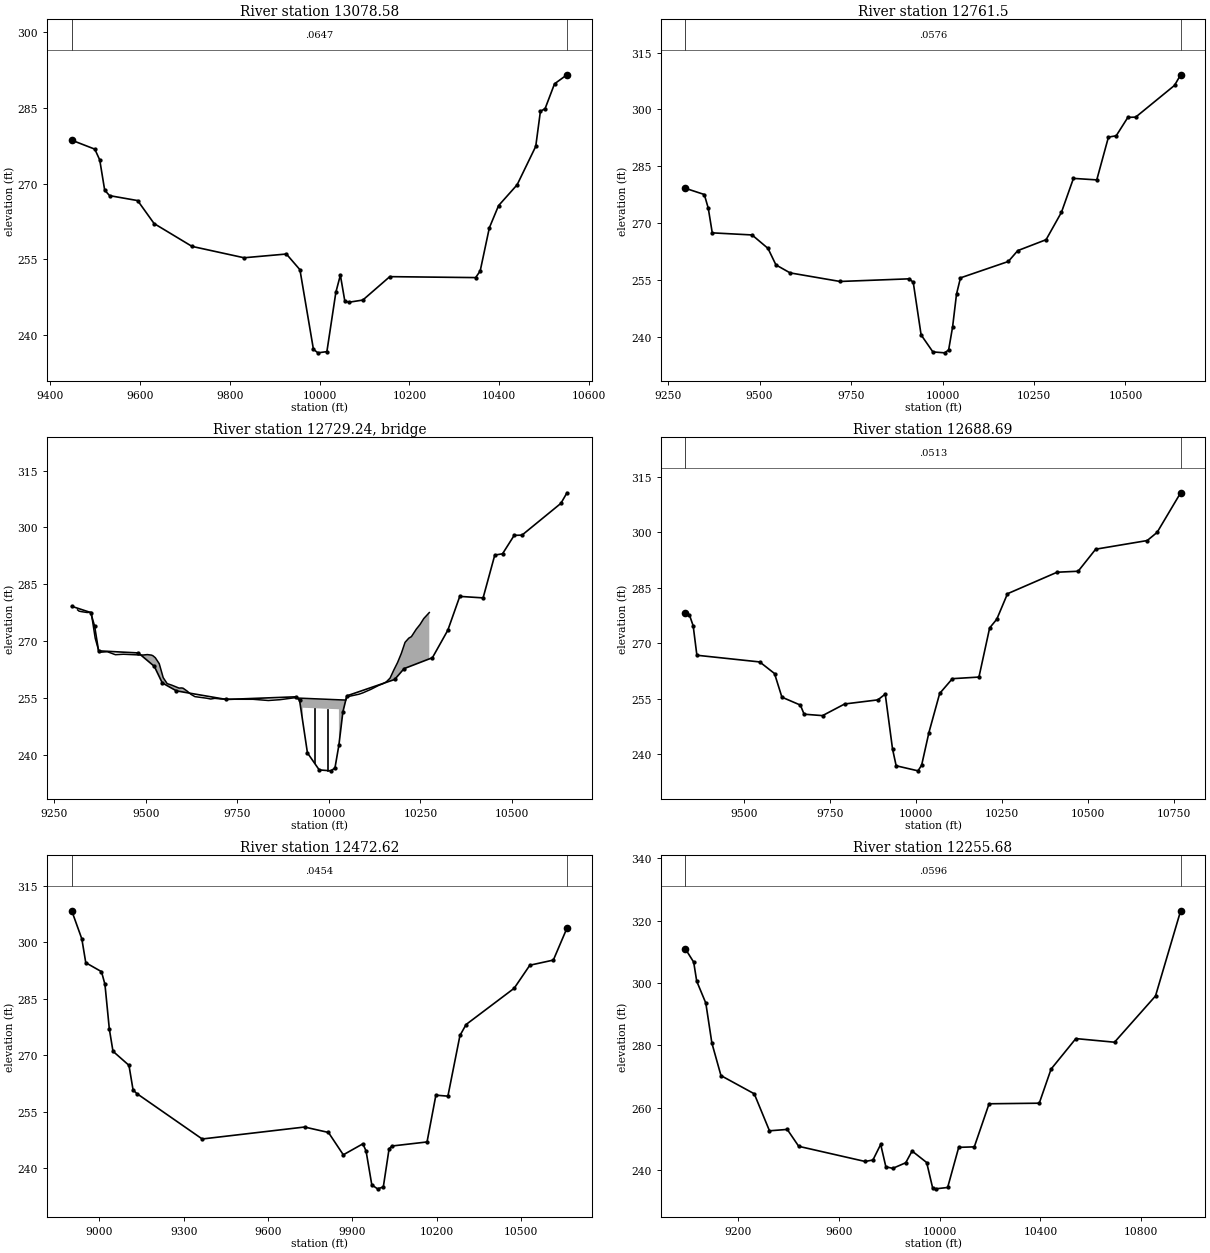
Type RM Length L Ch R = 1 ,13078.58,317.080800,317.080800,317.080800
XS GIS Cut Line= 6
695053.584111452840338.344970822695198.983417004840657.355387494
695250.589747339840734.488934755695603.944301367840742.747893751
695722.765662819840760.687595293695901.491798282840810.072857007
#Sta/Elev= 30
9447.797278.58119499.161276.80749510.171274.6676 9521.18268.6804 9532.19267.5949
9594.619 266.6189631.268262.06789715.678257.54699831.644255.29279925.956256.0353
9956.132252.92439986.185 237.1649996.187236.461610016.19236.7009 10036.2248.4691
10046.21 251.85510056.21246.670110066.22246.498310096.24246.914810156.29251.5523
10347.47251.364810357.64252.664510378.09261.225710398.61265.619610439.96269.7455
10481.44277.354410491.83284.298710502.31284.837810523.27289.744510551.04291.5364
#Mann= 3 , 0 , 0
9447.797  0.0647       09447.797  0.0647       010551.04  0.0647       0
#XS Ineff= 2 , 0
       0                               0
Bank Sta=9447.797,10551.04
Exp/Cntr=0.3,0.1

Type RM Length L Ch R = 1 , 12761.5,72.808800,72.808800,72.808800
XS GIS Cut Line= 6
695022.461558968840347.533711269695159.912625868840668.825580168
695234.565919667840873.139857933695347.413141847841157.862080127
695457.923158217841293.421033514695561.029357135841580.766178086
#Sta/Elev= 30
9297.313279.22199348.941277.58839359.817273.96239370.694267.48229479.461266.9305
9522.967263.39319544.721259.03769583.433256.93389719.872254.67259909.238255.3694
9919.974254.44389941.446240.59449973.653236.109110005.93235.8657 10016.7236.6496
10027.47242.675910038.24251.359610049.01 255.62110179.78259.937510205.58262.8019
10282.99265.680510325.01272.906610357.77281.834710421.51281.439410453.39292.7153
10474.63293.063210506.51297.922310527.76297.9724   10634306.340510650.75309.1374
#Mann= 3 , 0 , 0
9297.313  0.0576       09297.313  0.0576       010650.75  0.0576       0
#XS Ineff= 2 , 0
       0                               0
Bank Sta=9297.313,10650.75
Exp/Cntr=0.3,0.1

Type RM Length L Ch R = 3 ,12729.24,,,
BEGIN DESCRIPTION:
END DESCRIPTION:
Bridge Culvert--1,0,-1,-1, 0
Deck Dist Width WeirC Skew NumUp NumDn MinLoCord MaxHiCord MaxSubmerge Is_Ogee
14.914400,42.980000,2.6,0, 60, 60, , , 0.95, 0, 0,0,,
 9313.27 9317.32 9323.60 9339.37 9350.40 9361.42 9371.11 9372.45 9394.50 9416.54
 9438.59 9482.32 9493.15 9503.97 9514.80 9518.70 9525.63 9536.46 9547.29 9558.11
 9570.85 9590.60 9596.93 9601.42 9612.25 9623.00 9633.91 9666.39 9677.22 9688.05
 9704.25 9730.00 9792.76 9834.60 9865.98 9909.13 9910.16 9928.74 9928.7410027.49
10027.4910046.3410049.7610082.2210093.0310114.6710136.3010146.7510156.9910167.22
10177.4610187.7010197.9410208.1710218.4110225.6510238.8910249.1210259.3610274.44
  278.28  277.95  277.82  277.59  277.66  270.80  267.48  267.10  267.26  266.47
  266.59  266.40  266.39  266.50  266.37  266.23  265.68  264.10  260.42  258.85
  258.44  257.67  257.71  257.65  256.91  256.03  255.42  255.00  254.79  254.97
  254.82  254.73  254.72  254.40  254.61  255.16  255.06  254.99  254.99  254.59
  254.59  254.52  255.38  256.06  256.42  257.33  258.39  258.78  259.31  260.30
  262.43  264.40  266.79  269.72  270.83  271.24  273.20  274.43  276.00  277.57
 -721.72 -722.05 -722.18 -722.41 -722.34 -729.20 -732.52 -732.90 -732.74 -733.53
 -733.41 -733.60 -733.61 -733.50 -733.63 -733.77 -734.32 -735.90 -739.58 -741.15
 -741.56 -742.33 -742.29 -742.35 -743.09 -743.97 -744.58 -745.00 -745.21 -745.03
 -745.18 -745.27 -745.28 -745.60 -745.39 -744.84 -744.94 -745.01  252.49  252.09
 -745.41 -745.48 -744.62 -743.94 -743.58 -742.67 -741.61 -741.22 -740.69 -739.70
 -737.57 -735.60 -733.21 -730.28 -729.17 -728.76 -726.80 -725.57 -724.00 -722.43
 9313.27 9317.32 9323.60 9339.37 9350.40 9361.42 9371.11 9372.45 9394.50 9416.54
 9438.59 9482.32 9493.15 9503.97 9514.80 9518.70 9525.63 9536.46 9547.29 9558.11
 9570.85 9590.60 9596.93 9601.42 9612.25 9623.00 9633.91 9666.39 9677.22 9688.05
 9704.25 9730.00 9792.76 9834.60 9865.98 9909.13 9910.16 9932.47 9932.4710031.22
10031.2210046.3410049.7610082.2210093.0310114.6710136.3010146.7510156.9910167.22
10177.4610187.7010197.9410208.1710218.4110225.6510238.8910249.1210259.3610274.44
  278.28  277.95  277.82  277.59  277.66  270.80  267.48  267.10  267.26  266.47
  266.59  266.40  266.39  266.50  266.37  266.23  265.68  264.10  260.42  258.85
  258.44  257.67  257.71  257.65  256.91  256.03  255.42  255.00  254.79  254.97
  254.82  254.73  254.72  254.40  254.61  255.16  255.06  254.97  254.97  254.58
  254.58  254.52  255.38  256.06  256.42  257.33  258.39  258.78  259.31  260.30
  262.43  264.40  266.79  269.72  270.83  271.24  273.20  274.43  276.00  277.57
 -721.72 -722.05 -722.18 -722.41 -722.34 -729.20 -732.52 -732.90 -732.74 -733.53
 -733.41 -733.60 -733.61 -733.50 -733.63 -733.77 -734.32 -735.90 -739.58 -741.15
 -741.56 -742.33 -742.29 -742.35 -743.09 -743.97 -744.58 -745.00 -745.21 -745.03
 -745.18 -745.27 -745.28 -745.60 -745.39 -744.84 -744.94 -745.03  252.47  252.08
 -745.42 -745.48 -744.62 -743.94 -743.58 -742.67 -741.61 -741.22 -740.69 -739.70
 -737.57 -735.60 -733.21 -730.28 -729.17 -728.76 -726.80 -725.57 -724.00 -722.43
Pier Skew, UpSta & Num, DnSta & Num=  ,9961.16, 2 ,9964.88, 2 , 0 , 0 , 0 ,,
    3.00    3.00
 -745.14  254.86
    3.00    3.00
 -745.16  254.84
Pier Skew, UpSta & Num, DnSta & Num=  ,9995.08, 2 ,9998.80, 2 , 0 , 0 , 0 ,,
    3.00    3.00
 -745.28  254.72
    3.00    3.00
 -745.29  254.71
BR Coef=-1 , 0 , 0 ,, 0 ,,,0.8,0,1,0,
WSPro=,,,, 1 ,,,, 0 ,,,, 0 ,,,,-1 ,-1 ,-1 , 0 , 0 , 0 , 0 , 0
BC Design=,, 0 ,, 0 ,,,,,,

Type RM Length L Ch R = 1 ,12688.69,216.074100,216.074100,216.074100
XS GIS Cut Line= 6
694974.149252951840393.973191246695185.954808503840937.375969023
695229.357586324841064.112080127695311.828777164 841365.74597697
695356.348352581841593.290473506695419.736622095841758.917887509
#Sta/Elev= 30
9330.011278.16059341.858277.62699352.601274.70349363.344266.74919545.981264.9371
9588.954   261.89610.441255.39779664.157253.25259674.901250.78759728.511250.4046
 9792.81253.55659889.257254.6677 9910.69256.23069931.865 241.3829942.435236.8297
10005.86235.455310016.43236.977210037.57245.813910068.87256.407410105.81260.4064
10182.99 260.84210214.07274.144710234.79276.500310265.88283.401310410.09289.2276
10471.23289.491110522.18295.459110671.92297.800910700.67300.006810769.11310.7337
#Mann= 3 , 0 , 0
9330.011  0.0513       09330.011  0.0513       010769.11  0.0513       0
#XS Ineff= 2 , 0
       0                               0
Bank Sta=9330.011,10769.11
Exp/Cntr=0.3,0.1

Type RM Length L Ch R = 1 ,12472.62,216.939100,216.939100,216.939100
XS GIS Cut Line= 6
694332.396878541840229.270451605 694626.43389532840530.253224701
694955.927861452840963.378357589 694997.16632089841033.483738586
695094.336371213841360.229354307695282.065391809841684.408976704
#Sta/Elev= 30
8901.296308.38818937.266300.90828951.245294.59479007.165292.22019019.502288.8577
9035.125276.98179048.122271.07739105.024267.34069119.673260.79859132.984259.8431
9365.725247.77879730.102250.95549815.194249.51689868.158243.57539937.769246.4951
9949.165244.60179969.662235.58069990.158234.538410010.61235.038810031.06245.1296
10041.28 245.91210166.28246.9901 10197.8259.416210240.56259.152710283.49275.2716
10305.35278.183810476.46287.803710532.26293.928410615.97295.294110664.54303.7929
#Mann= 3 , 0 , 0
8901.296  0.0454       08901.296  0.0454       010664.54  0.0454       0
#XS Ineff= 2 , 0
       09670.493                       0
Bank Sta=8901.296,10664.54
Exp/Cntr=0.3,0.1

Type RM Length L Ch R = 1 ,12255.68,124.706400,124.706400,124.706400
XS GIS Cut Line= 6
694292.466322988840247.699938789694501.015186072840558.153359963
694693.333280772 840961.68152459695057.916614056841545.448885709
695238.642747557841734.863775583 695339.87551102841900.210622534
#Sta/Elev= 30
 8989.48310.92259022.368306.70669034.414300.59099070.555293.57189094.648280.7634
9130.789270.32559263.023264.49689323.538252.63159394.116253.07519439.767247.6554
9703.752242.79829734.592243.27279765.392248.26739785.926241.09869813.319240.5907
9864.871242.39069890.177 246.1519948.175242.45859971.976234.27729983.876234.0272
10031.48 234.46510075.41247.322410137.38247.485810196.05261.2957 10395.5261.4813
10442.43272.415910540.85282.1935 10694.5281.031410857.39 295.859 10957.3323.1645
#Mann= 3 , 0 , 0
 8989.48  0.0596       0 8989.48  0.0596       0 10957.3  0.0596       0
#XS Ineff= 2 , 0
       09761.567                       0
Bank Sta=8989.48,10957.3
Exp/Cntr=0.3,0.1

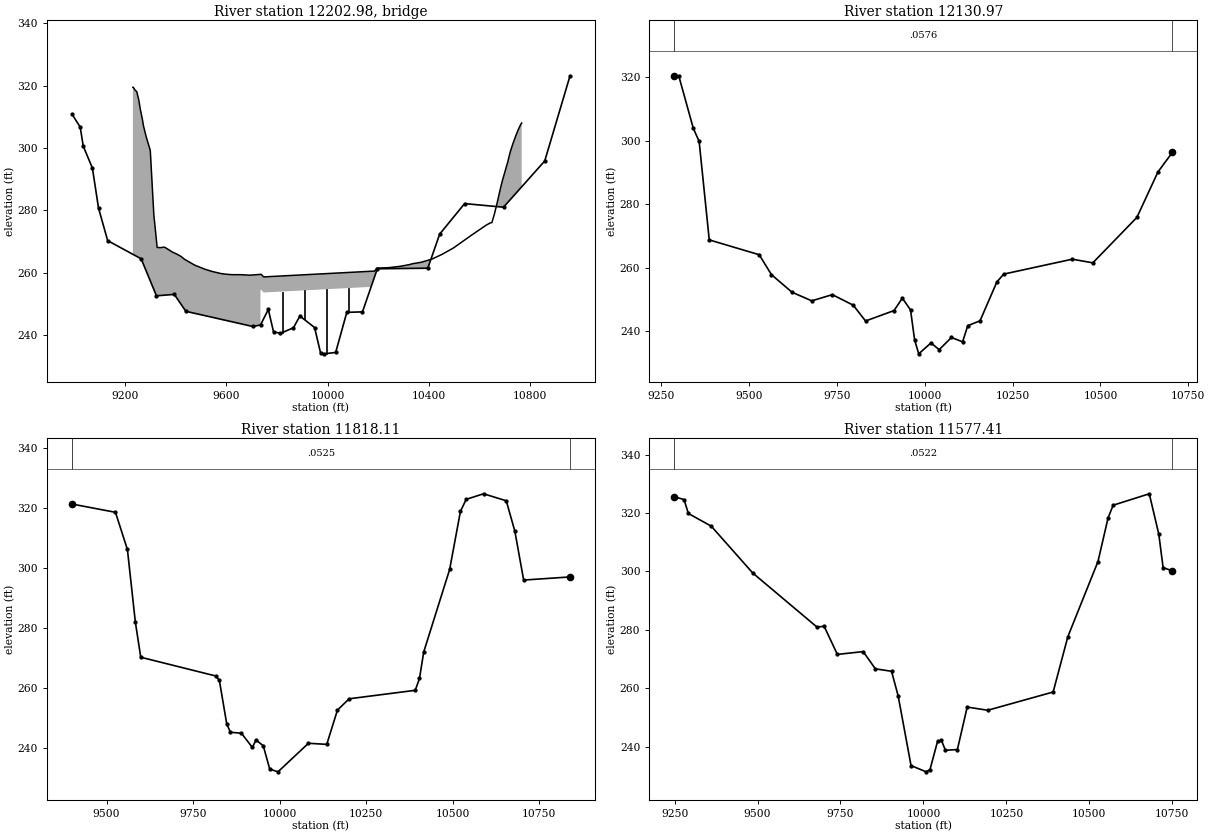
Type RM Length L Ch R = 3 ,12202.98,,,
BEGIN DESCRIPTION:
END DESCRIPTION:
Bridge Culvert--1,0,-1,-1, 0
Deck Dist Width WeirC Skew NumUp NumDn MinLoCord MaxHiCord MaxSubmerge Is_Ogee
37.583200,49.540000,2.6,0, 60, 60, , , 0.95, 0, 0,0,,
 9230.47 9232.09 9238.49 9245.56 9253.42 9259.03 9268.35 9272.50 9283.28 9298.21
 9299.43 9313.14 9326.37 9339.84 9353.31 9357.92 9387.78 9402.71 9420.65 9434.12
 9474.52 9514.93 9541.86 9577.65 9600.49 9623.34 9657.60 9691.86 9734.42 9734.42
 9737.55 9747.0010166.8310166.8310185.1610194.4910241.2410287.7710322.6610334.12
10369.1910412.4210451.5710497.1510567.4410626.2310637.9810639.2710648.5410658.94
10669.3510683.8310690.1610710.9710721.3810731.7910742.1910752.6010763.0010766.31
  319.47  319.50  318.62  318.10  315.56  312.76  309.04  307.03  303.53  299.53
  298.90  278.68  268.11  268.08  268.23  268.12  266.60  266.06  265.26  264.35
  262.47  261.15  260.47  259.78  259.53  259.40  259.40  259.24  259.50  259.50
  259.50  258.69  260.48  260.48  260.55  261.51  261.65  262.10  262.63  262.90
  263.38  264.42  265.91  267.99  272.03  275.29  275.80  275.94  276.09  278.94
  282.42  287.56  289.58  295.46  298.84  301.43  303.75  305.87  307.64  308.01
 -680.53 -680.50 -681.38 -681.90 -684.44 -687.24 -690.96 -692.97 -696.47 -700.47
 -701.10 -721.32 -731.89 -731.92 -731.77 -731.88 -733.40 -733.94 -734.74 -735.65
 -737.53 -738.85 -739.53 -740.22 -740.47 -740.60 -740.60 -740.76 -740.50  254.50
  254.50  253.69  255.48 -739.52 -739.45 -738.49 -738.35 -737.90 -737.37 -737.10
 -736.62 -735.58 -734.09 -732.01 -727.97 -724.71 -724.20 -724.06 -723.91 -721.06
 -717.58 -712.44 -710.42 -704.54 -701.16 -698.57 -696.25 -694.13 -692.36 -691.99
 9230.47 9232.09 9238.49 9245.56 9253.42 9259.03 9268.35 9272.50 9283.28 9298.21
 9299.43 9313.14 9326.37 9339.84 9353.31 9357.92 9387.78 9402.71 9420.65 9434.12
 9474.52 9514.93 9541.86 9577.65 9600.49 9623.34 9657.60 9691.86 9736.99 9747.00
 9771.57 9771.5710185.1610194.4910203.9810203.9810241.2410287.7710322.6610334.12
10369.1910412.4210451.5710497.1510567.4410626.2310637.9810639.2710648.5410658.94
10669.3510683.8310690.1610710.9710721.3810731.7910742.1910752.6010763.0010766.31
  319.47  319.50  318.62  318.10  315.56  312.76  309.04  307.03  303.53  299.53
  298.90  278.68  268.11  268.08  268.23  268.12  266.60  266.06  265.26  264.35
  262.47  261.15  260.47  259.78  259.53  259.40  259.40  259.24  259.51  258.69
  258.79  258.79  260.55  261.51  261.55  261.55  261.65  262.10  262.63  262.90
  263.38  264.42  265.91  267.99  272.03  275.29  275.80  275.94  276.09  278.94
  282.42  287.56  289.58  295.46  298.84  301.43  303.75  305.87  307.64  308.01
 -680.53 -680.50 -681.38 -681.90 -684.44 -687.24 -690.96 -692.97 -696.47 -700.47
 -701.10 -721.32 -731.89 -731.92 -731.77 -731.88 -733.40 -733.94 -734.74 -735.65
 -737.53 -738.85 -739.53 -740.22 -740.47 -740.60 -740.60 -740.76 -740.49 -741.31
 -741.21  253.79  255.55  256.51  256.55 -738.45 -738.35 -737.90 -737.37 -737.10
 -736.62 -735.58 -734.09 -732.01 -727.97 -724.71 -724.20 -724.06 -723.91 -721.06
 -717.58 -712.44 -710.42 -704.54 -701.16 -698.57 -696.25 -694.13 -692.36 -691.99
Pier Skew, UpSta & Num, DnSta & Num=  ,9819.70, 2 ,9856.85, 2 , 0 , 0 , 0 ,,
    4.00    4.00
 -741.00  259.00
    4.00    4.00
 -740.84  259.16
Pier Skew, UpSta & Num, DnSta & Num=  ,9906.99, 2 ,9944.13, 2 , 0 , 0 , 0 ,,
    4.00    4.00
 -740.63  259.37
    4.00    4.00
 -740.47  259.53
Pier Skew, UpSta & Num, DnSta & Num=  ,9994.27, 2 ,10031.41, 2 , 0 , 0 , 0 ,,
    4.00    4.00
 -740.26  259.74
    4.00    4.00
 -740.10  259.90
Pier Skew, UpSta & Num, DnSta & Num=  ,10081.55, 2 ,10118.69, 2 , 0 , 0 , 0 ,,
    4.00    4.00
 -739.89  260.11
    4.00    4.00
 -739.73  260.27
BR Coef=-1 , 0 , 0 ,, 0 ,,,0.8,0,1,0,
WSPro=,,,, 1 ,,,, 0 ,,,, 0 ,,,,-1 ,-1 ,-1 , 0 , 0 , 0 , 0 , 0
BC Design=,, 0 ,, 0 ,,,,,,

Type RM Length L Ch R = 1 ,12130.97,312.868900,312.868900,312.868900
XS GIS Cut Line= 4
694256.044227928 840546.06154035694424.110286653 840707.90293023
694953.624175549841595.489735797695018.195681646841732.459597185
#Sta/Elev= 30
9286.977320.42419299.863320.27239341.058303.8408 9357.53  299.799386.363268.7684
9528.562264.10139563.495257.82559621.717252.31369678.183249.58799736.739251.5373
9796.382248.20819831.315243.24129912.406246.52129936.114250.42889959.402246.7264
9971.047237.29989982.691232.904910017.62236.334610040.91234.219210075.85238.0542
10107.59236.683510122.42241.769610157.36243.308910205.18255.5235 10224.7257.9996
10419.89262.693810478.44261.545510603.96 275.85510663.85  290.1610705.26296.3561
#Mann= 3 , 0 , 0
9286.977  0.0576       09286.977  0.0576       010705.26  0.0576       0
#XS Ineff= 2 , 0
       09775.536                       0
Bank Sta=9286.977,10705.26
Exp/Cntr=0.3,0.1

Type RM Length L Ch R = 1 ,11818.11,240.693700,240.693700,240.693700
XS GIS Cut Line= 6
694113.438329115840647.989010724694253.083251868840893.257688274
694396.555802424841272.331658303694445.588147997841379.473492701
694564.796151037841559.610081865694818.547274401841890.518722921
#Sta/Elev= 30
9399.772321.24199525.636  318.489560.183306.07759583.073281.90949598.728270.1504
9815.083263.91129825.777262.46859847.167247.90519857.862245.13399889.548244.8194
9921.141240.06669931.672242.55439952.733240.62269971.323 232.8489995.173231.9373
10083.19 241.46610136.07241.096110166.98252.525710200.75256.298910391.77259.1221
10404.01263.079510416.26271.923110491.12299.424410522.31318.806710538.98322.7996
10589.01324.656610654.71322.322810679.54312.147110704.94295.884510838.93296.9292
#Mann= 3 , 0 , 0
9399.772  0.0525       09399.772  0.0525       010838.93  0.0525       0
#XS Ineff= 2 , 0
       09769.886         10240.8       0
Bank Sta=9399.772,10838.93
Exp/Cntr=0.3,0.1

Type RM Length L Ch R = 1 ,11577.41,240.693700,240.693700,240.693700
XS GIS Cut Line= 6
693645.970958919840811.946414791693957.945709943841161.567134342
 694091.97857251841266.252791337 694278.03380422841378.791541353
 694385.91276786841472.112828992694719.951093547841846.687207978
#Sta/Elev= 30
9249.086325.5787 9278.46324.59549291.202319.85579360.472315.48069485.473299.4457
9679.604 280.8839700.564281.23969740.547271.56529818.353272.52329855.158266.6245
 9903.89265.78919923.751257.3995 9962.67233.490610008.37 231.34310019.81232.1122
10042.71241.820310054.36242.115310066.38238.723210102.44238.976910131.95253.5344
10193.91252.437410391.11258.688610435.47277.652210526.23303.365410556.68 318.303
10571.93 322.66410680.93 326.588 10709.6312.762110722.64301.311610750.93300.1708
#Mann= 3 , 0 , 0
9249.086  0.0522       09249.086  0.0522       010750.93  0.0522       0
#XS Ineff= 2 , 0
       0                10298.17       0
Bank Sta=9249.086,10750.93
Exp/Cntr=0.3,0.1