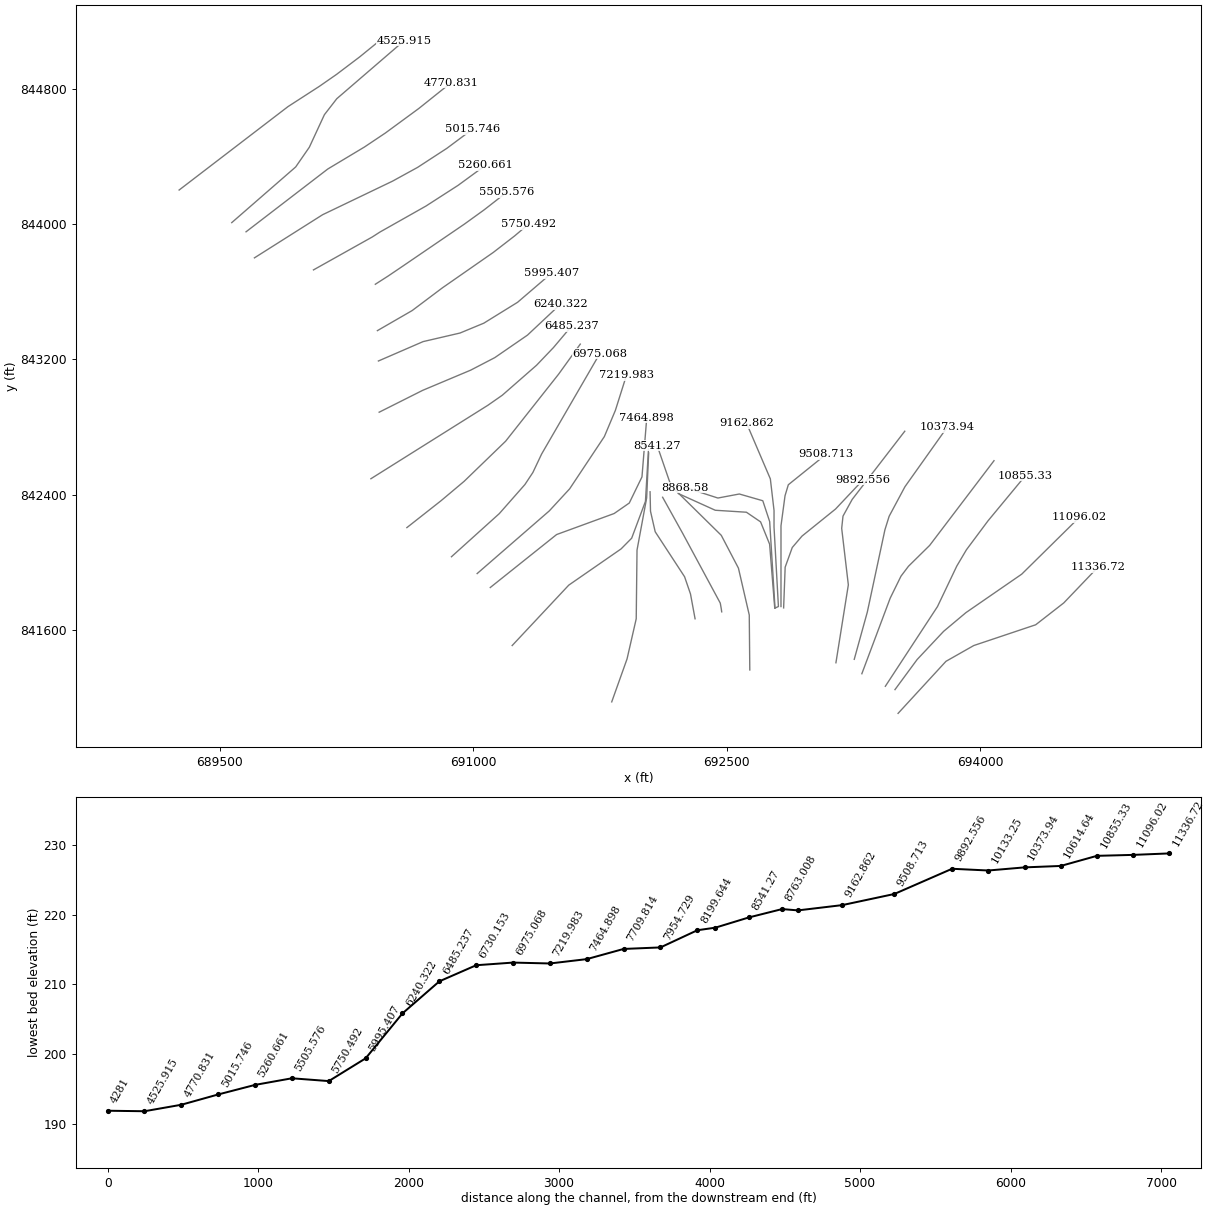
HEC-RAS study 13347_ras.prj: 13347

--- 13347_ras.g01 (geometry) --- (continued)

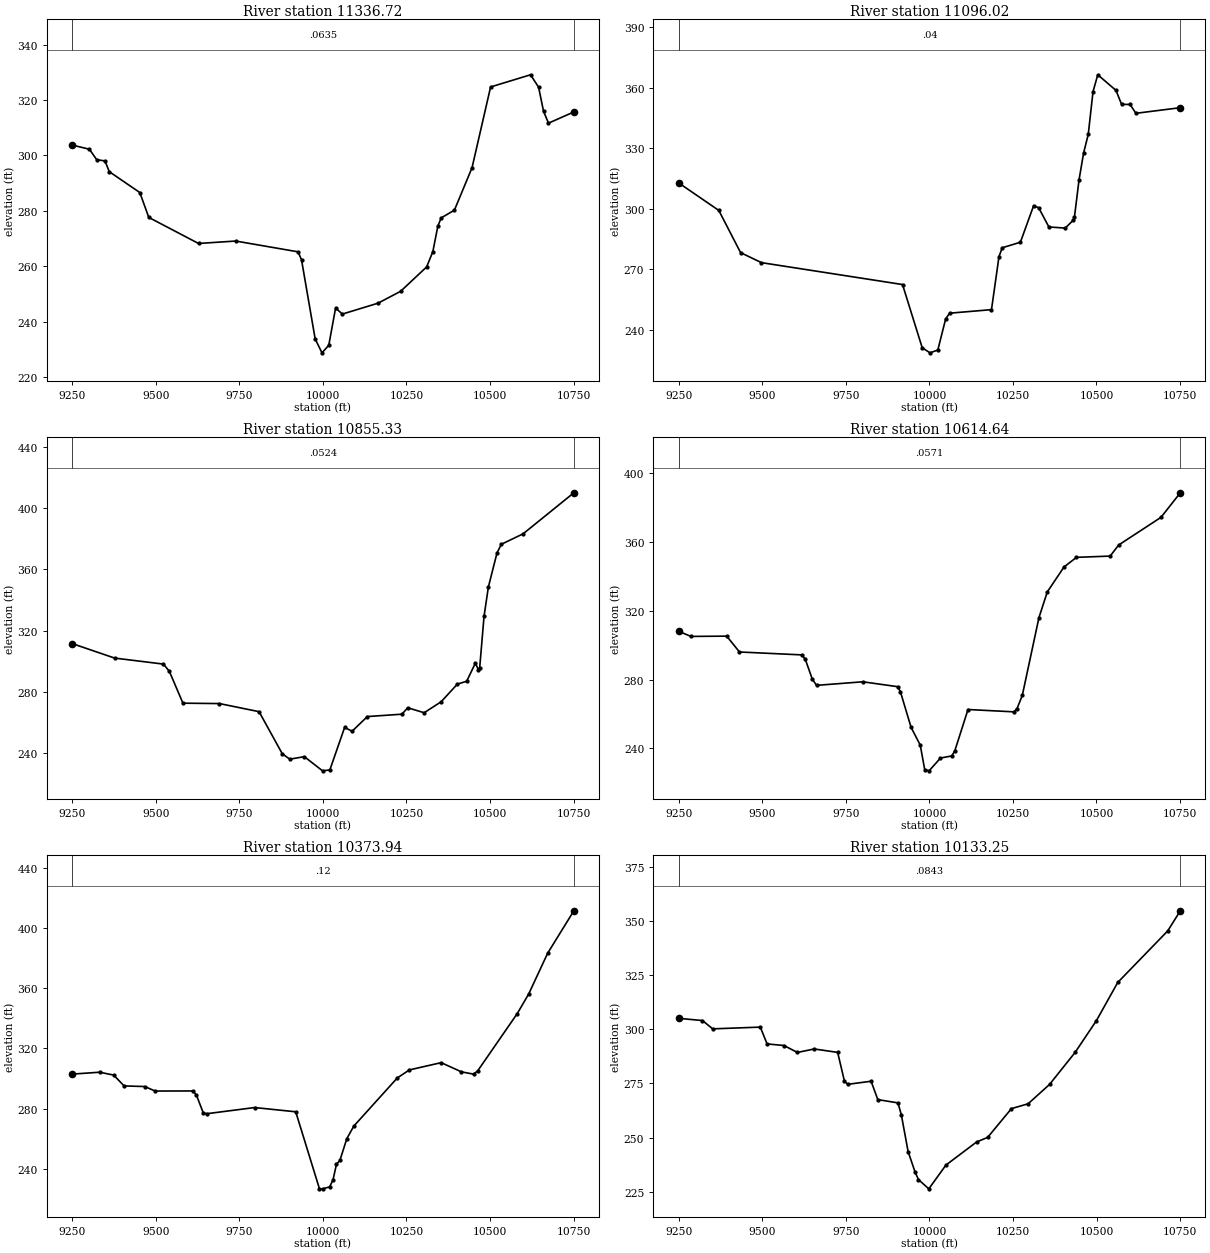
Type RM Length L Ch R = 1 ,11336.72,240.693700,240.693700,240.693700
XS GIS Cut Line= 6
693514.067984864841105.776269548693797.315131311841413.744123203
693962.057652351841507.236492791694328.312574169841630.029372789
694494.227510164 841759.20606393694696.395190018841970.467909232
#Sta/Elev= 30
9249.124303.76489301.096302.23859322.821298.46499347.709298.03139360.351294.1521
9451.855286.62569478.705277.64359627.518 268.2379738.898269.11359925.463265.2219
9935.856262.32939976.697233.78079997.081228.770910017.41231.506910037.74244.9083
10058.41242.770410164.67246.684110232.47250.979610310.39259.792910328.89265.3126
10343.83274.498110353.85277.469210393.38280.250510446.21295.597410501.68324.7129
10621.25329.110710645.36324.612710660.14315.943210674.92311.650410750.89315.6997
#Mann= 3 , 0 , 0
9249.124  0.0635       09249.124  0.0635       010750.89  0.0635       0
#XS Ineff= 2 , 0
       0                10321.67       0
Bank Sta=9249.124,10750.89
Exp/Cntr=0.3,0.1

Type RM Length L Ch R = 1 ,11096.02,240.693700,240.693700,240.693700
XS GIS Cut Line= 6
693495.669046827841246.347700184693626.702482956841424.302417276
693783.401839948841591.087843958693915.660824351841702.014739754
694245.758239321 841929.62308342694585.656142489 842264.82768686
#Sta/Elev= 30
9249.076312.8916  9369.6299.20779434.843278.25889497.273273.29549919.482262.4385
  9978.4231.087310001.75228.559210025.15 229.96110048.64245.423210060.61248.2318
10185.78249.982110208.16276.282910217.94280.680110272.28283.415610312.03301.6165
 10327.1300.485610357.55290.997210406.51290.439910430.55294.373910433.98 295.786
10447.71314.245810461.44327.669810475.42336.960510489.65358.125410503.89366.4818
10558.41358.734510575.06351.839910600.57351.740110618.08347.370910750.96350.1593
#Mann= 3 , 0 , 0
9249.076    0.04       09249.076    0.04       010750.96    0.04       0
#XS Ineff= 2 , 0
       0                               0
Bank Sta=9249.076,10750.96
Exp/Cntr=0.3,0.1

Type RM Length L Ch R = 1 ,10855.33,240.693800,240.693800,240.693800
XS GIS Cut Line= 6
693438.631803916841266.046596852693747.180977886841737.668675665
693861.450887049841977.452752456693918.368186074842073.657418034
694045.955528435842244.764965634694267.255016626842512.082028769
#Sta/Elev= 30
9249.041311.59239376.436302.09899522.486298.16899540.104 293.4999580.874272.6321
 9690.19272.37559808.741267.08149878.128239.62949900.523236.03649944.244237.6878
9998.801228.423610020.62229.0291 10064.8256.759410087.24254.314210132.96263.8956
10236.42265.436110253.69269.643210302.86266.382110353.54273.517510402.37285.1061
10430.19286.945310456.16298.795610465.15294.527310469.14295.881110482.12329.3634
 10495.1 348.56610521.07370.911810534.05376.466610598.96383.281610750.96 410.104
#Mann= 3 , 0 , 0
9249.041  0.0524       09249.041  0.0524       010750.96  0.0524       0
#XS Ineff= 2 , 0
       0                               0
Bank Sta=9249.041,10750.96
Exp/Cntr=0.3,0.1

Type RM Length L Ch R = 1 ,10614.64,240.693700,240.693700,240.693700
XS GIS Cut Line= 6
693299.679900829 841340.38332562693467.282663545 841787.32549523
693531.324732417841917.707880964693575.430642003841976.065950174
693700.873287002842099.664208562694081.613247404842600.811833757
#Sta/Elev= 30
9249.098308.14689286.192305.1184 9393.35  305.289431.464296.06739617.348 294.385
 9628.01292.06179649.333280.3327 9662.18276.6667 9800.54278.73879905.064275.8954
9913.254272.89919945.076252.27799972.592241.90439985.906227.67289998.968226.9734
10033.09234.4095 10066.9 235.63810075.84238.542210115.46262.628810252.96261.2661
10262.22263.171110277.92270.782510327.82316.059110352.78330.985310402.68345.4439
10440.11351.084810540.98351.815310566.31358.247510692.93374.324610750.94388.6183
#Mann= 3 , 0 , 0
9249.098  0.0571       09249.098  0.0571       010750.94  0.0571       0
#XS Ineff= 2 , 0
       0                               0
Bank Sta=9249.098,10750.94
Exp/Cntr=0.3,0.1

Type RM Length L Ch R = 1 ,10373.94,240.693700,240.693700,240.693700
XS GIS Cut Line= 6
  693254.6949846841425.529615966693332.029979949841705.285317974
693436.209360119842192.117204833693461.146752178842271.959658641
693554.707072165842446.937237959 693804.35899483842798.452397473
#Sta/Elev= 30
9249.025302.93989331.847304.20389373.534302.28119404.777295.10129466.735294.6882
9497.713291.69969610.819291.75489621.076289.1089 9641.59277.26679651.847276.6364
9795.444280.73759918.436277.92769989.515226.7863    9999226.767910019.93228.0598
10030.09232.7536 10040.3243.020710050.66245.623810071.36 260.09410092.44268.4664
10222.65300.442510258.81305.739610353.77310.548410414.39304.441310450.76302.9249
10462.89305.040110581.65343.170410615.72356.142110672.56383.223910750.93411.3876
#Mann= 3 , 0 , 0
9249.025    0.12       09249.025    0.12       010750.93    0.12       0
#XS Ineff= 2 , 0
       0                               0
Bank Sta=9249.025,10750.93
Exp/Cntr=0.3,0.1

Type RM Length L Ch R = 1 ,10133.25,240.693700,240.693700,240.693700
XS GIS Cut Line= 6
693146.293899039841405.177121923693219.735631733 841866.07829705
693180.392400204842200.484220541693188.140318204842272.843922249
693242.363661851842371.487696515693553.570357002842775.161298973
#Sta/Elev= 30
9249.128305.01339320.716303.97159351.475300.1454 9493.84300.95019514.141293.1933
9564.565292.46079604.905289.25489655.178 290.8649725.365289.28619745.367276.1664
9755.367274.54759825.425275.97049845.473267.50349905.824265.97839915.953260.4325
 9936.21243.49949956.712234.2101 9967.06230.59989998.104226.320910049.35237.2847
10141.29247.957410174.07250.043410245.45263.341810295.17265.555310359.35274.4794
10435.92289.266210499.72303.9418 10563.5321.545310713.21345.360210750.84354.6306
#Mann= 3 , 0 , 0
9249.128  0.0843       09249.128  0.0843       010750.84  0.0843       0
#XS Ineff= 2 , 0
       0                               0
Bank Sta=9249.128,10750.84
Exp/Cntr=0.3,0.1

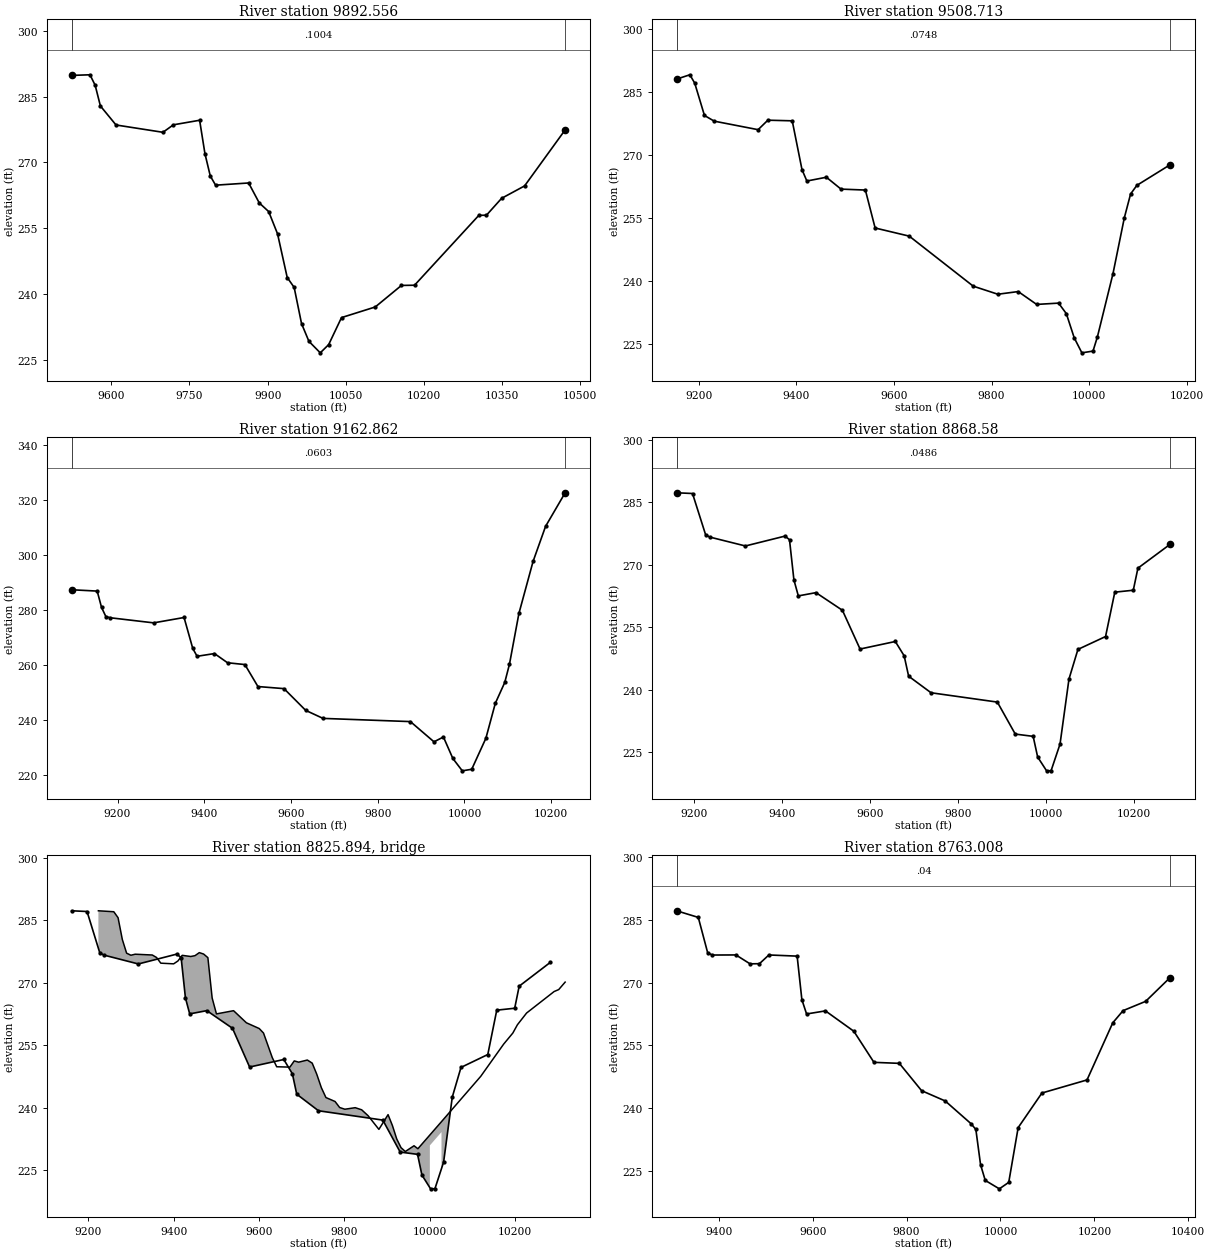
Type RM Length L Ch R = 1 ,9892.556,383.842500,383.842500,383.842500
XS GIS Cut Line= 6
 692836.86515076841729.846413909692845.936194054841970.803821962
692888.011579722842087.295767735692945.558041443842154.682671884
693144.081529535842314.867515495693306.738316167842487.183372706
#Sta/Elev= 30
9523.853289.82769559.006289.97019569.006287.57339579.006282.86379609.007278.5233
9699.055276.85539719.083278.5611 9769.47 279.6019779.689271.97419789.909266.8971
9800.129264.79819863.515265.30039883.945260.74669901.982258.78239919.004253.7064
9937.561243.74739950.919 241.4839965.051233.24129979.221229.1953   10001226.5693
10017.14228.448510041.77234.604410106.57237.0275 10156.8241.939910181.92241.9849
10305.38 257.92410319.95257.951410349.08261.802910393.14264.6302   10471277.4049
#Mann= 3 , 0 , 0
9523.853  0.1004       09523.853  0.1004       0   10471  0.1004       0
#XS Ineff= 2 , 0
       0                               0
Bank Sta=9523.853,10471
Exp/Cntr=0.3,0.1

Type RM Length L Ch R = 1 ,9508.713,345.850900,345.850900,345.850900
XS GIS Cut Line= 5
692821.240367979841737.961988762692821.240367979842215.392544329
 692845.11189577842393.343933225 692864.64314577842458.448099867
693088.167451322842638.569627658
#Sta/Elev= 30
9154.304288.12029181.342289.15349191.342287.17549211.342279.46479231.342278.1136
9321.342276.08229341.342 278.3419391.342278.19069411.342266.57949421.342263.8577
9461.342264.76129491.342261.93479541.342261.70739561.342252.67459631.342250.7364
9762.502238.82549813.008236.9052 9854.77237.54149892.551234.48069937.504234.7907
9953.442232.28849969.608226.52769985.316222.952610008.14223.371810017.19226.7669
10049.07241.788610072.35255.088710085.19260.765410098.03 262.82210166.32267.7383
#Mann= 3 , 0 , 0
9154.304  0.0748       09154.304  0.0748       010166.32  0.0748       0
#XS Ineff= 2 , 0
       0                               0
Bank Sta=9154.304,10166.32
Exp/Cntr=0.3,0.1

Type RM Length L Ch R = 1 ,9162.862,294.281800,294.281800,294.281800
XS GIS Cut Line= 6
 692786.17120856 841728.97238043  692806.0493958841737.961988762
692780.007729083842208.882127643692780.110718757842306.016072959
692758.306340188842493.170322105692617.247312427 842823.03143321
#Sta/Elev= 30
9094.278287.2641 9153.17286.77779163.181280.83239173.191277.49199183.201277.0708
9283.322275.21549353.446277.16689373.482265.9108  9383.5263.04999423.571264.0403
9453.624260.69769493.695260.03569523.748252.04169583.854251.27869633.861 243.368
9673.861240.44659875.291239.28319929.671231.92269951.423233.67719973.175 225.856
9994.926221.360610016.68221.933310049.31233.210710071.06 245.94110092.81253.5244
10103.69260.181310125.44278.631610158.07297.556210186.91310.330210232.06322.5566
#Mann= 3 , 0 , 0
9094.278  0.0603       09094.278  0.0603       010232.06  0.0603       0
#XS Ineff= 2 , 0
       0                               0
Bank Sta=9094.278,10232.06
Exp/Cntr=0.3,0.1

Type RM Length L Ch R = 1 , 8868.58,105.572000,105.572000,105.572000
XS GIS Cut Line= 6
692785.853870064841728.966909066692754.350245148842240.253292277
692713.601479113842363.830044314692574.712590218842403.760599867
692447.960875183 842379.90145354  692255.2681458842441.955044314
#Sta/Elev= 30
9160.752287.25979196.816287.08569226.842277.11779236.852276.62049317.044274.5089
9407.259 276.8799417.283275.99869427.306266.3808 9437.33262.53989477.426263.3206
9537.569259.08839577.665249.80199657.819251.60989677.903248.17999688.077243.2931
9739.032239.31999889.759237.08419930.465229.41479971.169  228.879981.345 223.922
 10001.7220.603510011.87220.627710032.22227.012810052.57242.613610072.93249.7128
10135.73252.799610156.74263.435710198.76263.898310209.27269.186610282.53274.9181
#Mann= 3 , 0 , 0
9160.752  0.0486       09160.752  0.0486       010282.53  0.0486       0
#XS Ineff= 2 , 0
       0                               0
Bank Sta=9160.752,10282.53
Exp/Cntr=0.3,0.1

Type RM Length L Ch R = 3 ,8825.894,,,
BEGIN DESCRIPTION:
END DESCRIPTION:
Bridge Culvert--1,0,-1,-1, 0
Deck Dist Width WeirC Skew NumUp NumDn MinLoCord MaxHiCord MaxSubmerge Is_Ogee
44.421000,16.730000,2.6,0, 60, 60, , , 0.95, 0, 0,0,,
 9223.40 9259.48 9269.49 9279.50 9289.51 9299.52 9309.54 9349.59 9359.61 9369.64
 9399.72 9409.75 9419.77 9439.83 9449.85 9459.88 9469.90 9479.93 9489.96 9499.98
 9540.09 9570.17 9600.25 9610.28 9630.85 9641.14 9672.02 9682.31 9692.60 9712.94
 9724.34 9735.06 9745.77 9756.49 9777.91 9788.63 9800.88 9825.14 9840.23 9855.32
 9880.59 9902.08 9912.37 9922.42 9932.47 9942.51 9962.87 9971.9410000.0010000.00
10027.2310027.2310119.1810172.9210194.4110205.1610226.6510291.1410301.8810316.97
  287.26  287.03  285.60  280.37  277.10  276.60  276.85  276.66  276.07  274.70
  274.54  275.23  276.58  276.30  276.51  277.23  276.89  276.02  266.34  262.54
  263.31  260.41  259.03  257.95  252.05  249.87  249.78  251.27  250.97  251.48
  250.74  248.07  244.86  242.49  241.54  240.10  239.69  240.06  239.55  238.13
  234.86  238.39  235.75  232.55  230.47  229.55  230.93  230.22  233.51  233.51
  236.71  236.71  247.57  255.30  257.95  259.94  262.75  267.90  268.37  270.16
 -712.74 -712.97 -714.40 -719.63 -722.90 -723.40 -723.15 -723.34 -723.93 -725.30
 -725.46 -724.77 -723.42 -723.70 -723.49 -722.77 -723.11 -723.98 -733.66 -737.46
 -736.69 -739.59 -740.97 -742.05 -747.95 -750.13 -750.22 -748.73 -749.03 -748.52
 -749.26 -751.93 -755.14 -757.51 -758.46 -759.90 -760.31 -759.94 -760.45 -761.87
 -765.14 -761.61 -764.25 -767.45 -769.53 -770.45 -769.07 -769.78 -766.49  231.01
  234.21 -763.29 -752.43 -744.70 -742.05 -740.06 -737.25 -732.10 -731.63 -729.84
 9223.40 9259.48 9269.49 9279.50 9289.51 9299.52 9309.54 9349.59 9359.61 9369.64
 9399.72 9409.75 9419.77 9439.83 9449.85 9459.88 9469.90 9479.93 9489.96 9499.98
 9540.09 9570.17 9600.25 9610.28 9630.85 9641.14 9672.02 9682.31 9692.60 9712.94
 9724.34 9735.06 9745.77 9756.49 9777.91 9788.63 9800.88 9825.14 9840.23 9855.32
 9880.59 9902.08 9912.37 9922.42 9932.47 9942.51 9962.87 9971.9410000.0010000.00
10027.2310027.2310119.1810172.9210194.4110205.1610226.6510291.1410301.8810316.97
  287.26  287.03  285.60  280.37  277.10  276.60  276.85  276.66  276.07  274.70
  274.54  275.23  276.58  276.30  276.51  277.23  276.89  276.02  266.34  262.54
  263.31  260.41  259.03  257.95  252.05  249.87  249.78  251.27  250.97  251.48
  250.74  248.07  244.86  242.49  241.54  240.10  239.69  240.06  239.55  238.13
  234.86  238.39  235.75  232.55  230.47  229.55  230.93  230.22  233.51  233.51
  236.71  236.71  247.57  255.30  257.95  259.94  262.75  267.90  268.37  270.16
 -712.74 -712.97 -714.40 -719.63 -722.90 -723.40 -723.15 -723.34 -723.93 -725.30
 -725.46 -724.77 -723.42 -723.70 -723.49 -722.77 -723.11 -723.98 -733.66 -737.46
 -736.69 -739.59 -740.97 -742.05 -747.95 -750.13 -750.22 -748.73 -749.03 -748.52
 -749.26 -751.93 -755.14 -757.51 -758.46 -759.90 -760.31 -759.94 -760.45 -761.87
 -765.14 -761.61 -764.25 -767.45 -769.53 -770.45 -769.07 -769.78 -766.49  231.01
  234.21 -763.29 -752.43 -744.70 -742.05 -740.06 -737.25 -732.10 -731.63 -729.84
BR Coef=-1 , 0 , 0 ,, 0 ,,,0.8,0,1,0,
WSPro=,,,, 1 ,,,, 0 ,,,, 0 ,,,,-1 ,-1 ,-1 , 0 , 0 , 0 , 0 , 0
BC Design=,, 0 ,, 0 ,,,,,,

Type RM Length L Ch R = 1 ,8763.008,221.738700,221.738700,221.738700
XS GIS Cut Line= 6
692784.268655479841728.939577788692753.875877738842107.078457132
692700.546215683842238.788832545692616.599400789842295.919303805
692432.382779211842307.578583643692213.677505881842406.490516305
#Sta/Elev= 30
 9310.32287.12349356.431285.54059376.459277.07869386.473276.56579436.557276.5897
9466.639274.46569486.694 274.5019506.749276.58259566.962276.30549577.007265.9361
9587.052262.50479627.231263.24419687.725258.38329730.531250.96529784.632250.7258
9832.012244.21119882.282241.75639937.597236.3049  9947.6234.95129957.603226.5536
9967.606222.80259997.615220.791810017.62222.336810037.69235.394910088.32243.6505
10184.33246.769610239.21260.397410261.16263.300910309.23265.517110361.39271.2054
#Mann= 3 , 0 , 0
 9310.32    0.04       0 9310.32    0.04       010361.39    0.04       0
#XS Ineff= 2 , 0
       0                               0
Bank Sta=9310.32,10361.39
Exp/Cntr=0.3,0.1

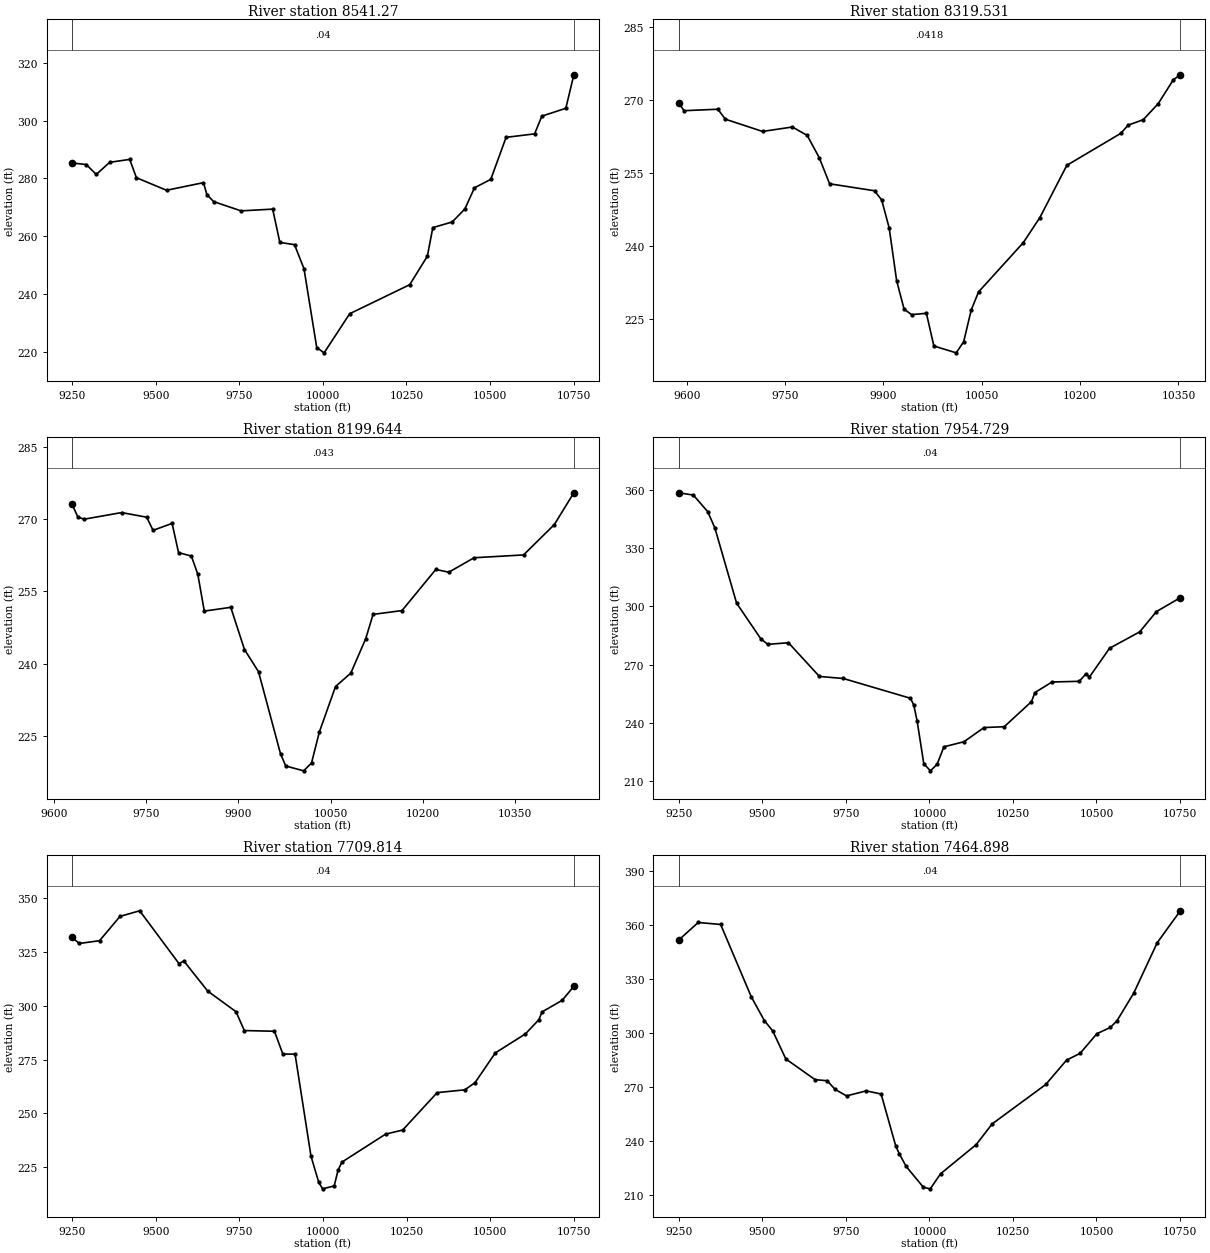
Type RM Length L Ch R = 1 , 8541.27,221.738800,221.738800,221.738800
XS GIS Cut Line= 6
 692636.66527704841362.624593652692633.545989738841687.542780176
692569.437054672841965.140273088692467.977657062842159.204967787
692170.708560878842451.846191404 692089.20346814842688.655318008
#Sta/Elev= 30
9249.091285.31289291.525284.79429321.566281.35589361.603285.55289421.614286.5646
9441.622280.22589531.758275.87229642.432278.51299652.601274.34629672.961271.9449
9754.861  268.749849.471269.3462    9871257.7979  9914.8257.05229943.286248.6784
9981.343 221.41610003.46219.587710079.94 233.12610259.69243.181810312.32253.0318
10328.79262.940810386.73264.895210424.74269.399510453.41 276.72610502.28279.6637
10548.07294.196510633.43295.405510655.09301.534510726.79304.259710750.89315.8605
#Mann= 3 , 0 , 0
9249.091    0.04       09249.091    0.04       010750.89    0.04       0
#XS Ineff= 2 , 0
       0                               0
Bank Sta=9249.091,10750.89
Exp/Cntr=0.3,0.1

Type RM Length L Ch R = 1 ,8319.531,119.886900,119.886900,119.886900
XS GIS Cut Line= 5
692470.410208672 841706.58301121692468.204089642 841722.95774053
692461.966187268841758.252323821692240.294187427842169.602613762
692120.936548531842384.446363762
#Sta/Elev= 30
9587.449269.47929595.942267.85819647.478268.15679658.838266.11059715.636263.5944
9761.074264.50839783.793262.76929802.055258.21519817.872252.84419886.374251.4126
9897.389 249.5049908.749243.77069920.108232.97339931.468227.11719942.827225.9716
9965.547226.24789976.906219.532410010.98218.127210022.34220.389810033.93 226.937
10045.06230.636410113.26240.748110138.58245.897410179.77 256.64110261.98 263.196
10273.42264.9007 10296.3266.006110319.18269.311210342.06274.177310352.86275.2321
#Mann= 3 , 0 , 0
9587.449  0.0418       09587.449  0.0418       010352.86  0.0418       0
#XS Ineff= 2 , 0
       0                               0
Bank Sta=9587.449,10352.86
Exp/Cntr=0.3,0.1

Type RM Length L Ch R = 1 ,8199.644,244.915200,244.915200,244.915200
XS GIS Cut Line= 6
692312.923902843841665.394285068692285.794599028841812.278575652
692250.787639368841914.224922261692076.962706861842180.319245214
692049.191245035842301.691990963692046.642690938 842416.82751528
#Sta/Elev= 30
9629.472273.04259639.133270.37319649.223269.96879710.033271.34099750.963270.3798
9761.225267.65269792.255269.0916 9802.71263.03839823.619262.31079834.073258.5284
9844.641250.90079887.696251.6793 9909.99242.92429932.861238.32429968.622221.3024
9977.132218.761910006.31217.756710019.09219.378910031.88225.835810058.16235.2527
10083.02238.029810107.27 245.17110119.24250.2204 10166.3251.005610221.32259.5373
 10242.5258.972710283.65 261.968 10364.1262.552410414.12268.843710445.95275.4473
#Mann= 3 , 0 , 0
9629.472   0.043       09629.472   0.043       010445.95   0.043       0
#XS Ineff= 2 , 0
       0                               0
Bank Sta=9629.472,10445.95
Exp/Cntr=0.3,0.1

Type RM Length L Ch R = 1 ,7954.729,244.915300,244.915300,244.915300
XS GIS Cut Line= 6
691819.769491291841173.771440111691910.393839615841427.769425469
691964.700988281841665.366657661691969.433777657842071.809724366
692026.386663041842380.059528588692038.291294567842646.560152909
#Sta/Elev= 30
9249.077358.44419293.345357.27429336.294348.75939357.768340.36929422.888301.6021
9494.977283.34859515.964280.42769578.095281.2322 9670.81263.88049742.069 262.842
9943.099252.66049953.101249.18699963.102241.03229983.109 218.97610003.16215.2951
10023.22218.765510043.27227.649910103.43230.288810163.44  237.5810223.85238.0096
10305.48250.930410315.72255.5982 10366.9261.032310448.37261.385410468.66265.2734
 10478.8 263.59410539.13278.407310629.33286.837910679.35297.270210750.91304.4276
#Mann= 3 , 0 , 0
9249.077    0.04       09249.077    0.04       010750.91    0.04       0
#XS Ineff= 2 , 0
       0                               0
Bank Sta=9249.077,10750.91
Exp/Cntr=0.3,0.1

Type RM Length L Ch R = 1 ,7709.814,244.915200,244.915200,244.915200
XS GIS Cut Line= 6
 691230.81402077841507.199296832691565.557958657 841864.50534283
691875.332347629842079.038781165691937.795754344842142.249757401
692019.272562282842360.059989567692037.337558404842669.964955731
#Sta/Elev= 30
9249.061331.64689270.578328.79859331.251 330.0789392.568 341.3469451.401343.9511
9569.018319.46869583.725320.65359655.029306.73249739.686297.16719764.577288.4431
9854.789288.1106 9879.85277.56019916.465277.5127 9964.14230.20379987.379218.0716
9998.968215.077410033.57216.422210045.11223.720110056.65 227.45910187.16240.4185
10238.53242.334210341.77259.669910424.49260.962710455.08264.278510515.65278.0575
10605.88286.885310645.89293.428610655.89297.102910715.89302.447310750.86308.9492
#Mann= 3 , 0 , 0
9249.061    0.04       09249.061    0.04       010750.86    0.04       0
#XS Ineff= 2 , 0
       0                               0
Bank Sta=9249.061,10750.86
Exp/Cntr=0.3,0.1

Type RM Length L Ch R = 1 ,7464.898,244.915300,244.915300,244.915300
XS GIS Cut Line= 6
691101.150020595841850.475683487691493.633475615842163.827834308
  691834.0956394842288.233264602691923.619328408 842350.39323171
691998.714165187 842504.90490634692026.976563108842854.179225913
#Sta/Elev= 30
9249.133351.74199307.997 361.5979375.116360.50289466.895 320.2749506.016 307.071
 9530.98 301.3659570.183285.79419657.762274.27959693.862273.67439717.796268.8666
9752.062 265.2499810.706268.04149855.394266.30249898.904237.63149909.543 233.168
9930.459226.04919982.137214.4512 10002.6213.618110033.38221.9994 10139.9238.1802
10188.03249.730510348.14271.588110410.39285.128110450.98 288.89310501.29299.8273
10541.48303.286410561.51307.043110611.57322.387210681.65350.323910750.91368.0984
#Mann= 3 , 0 , 0
9249.133    0.04       09249.133    0.04       010750.91    0.04       0
#XS Ineff= 2 , 0
       0                               0
Bank Sta=9249.133,10750.91
Exp/Cntr=0.3,0.1

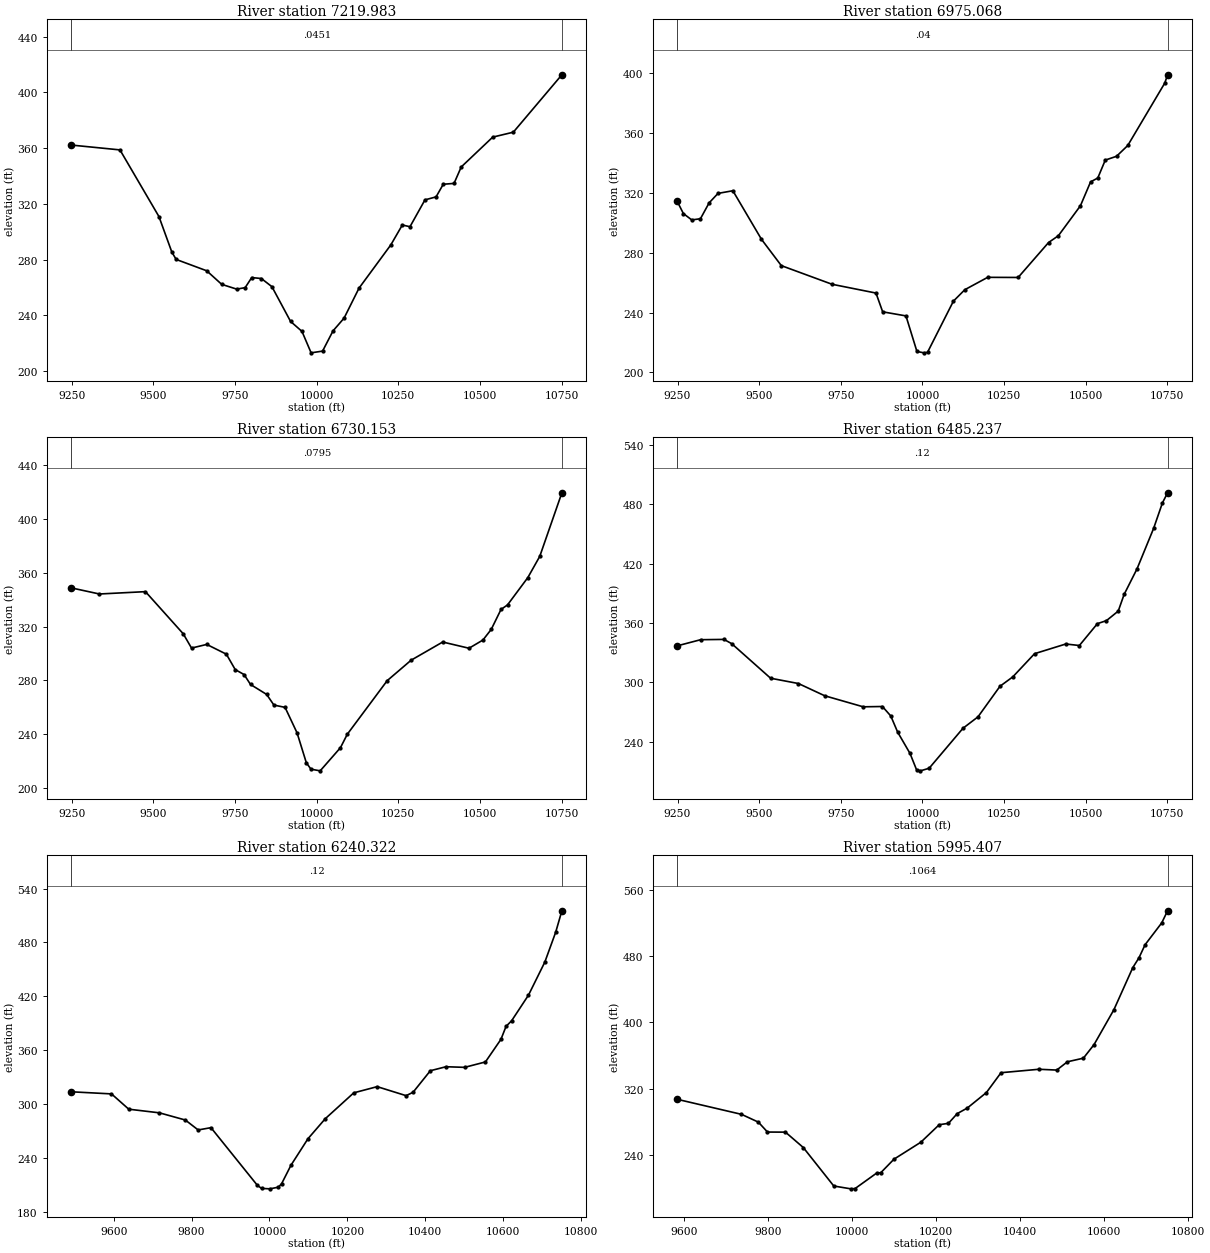
Type RM Length L Ch R = 1 ,7219.983,244.915200,244.915200,244.915200
XS GIS Cut Line= 6
691023.566595577841933.015814594691450.221494518842303.632257923
691570.868288608842434.385146997691776.138035769842743.413827887
691841.417738383842898.552985005691907.266846246843107.075518876
#Sta/Elev= 30
9249.046362.16279397.468358.70229516.867310.83679556.472285.25739569.674280.0553
9663.125271.91129709.076262.16729755.027258.73739780.903 259.8029800.978267.0332
9830.448266.36459862.875260.49789920.075235.5272 9954.93228.38659982.905212.9945
   10018214.243410049.99 228.75110083.82237.898710129.58259.418310227.02290.4914
10262.23304.773510285.71303.548110331.61322.826410365.61324.972210387.64334.0403
10420.68 334.64810442.64346.439610539.05367.872510602.23371.420610750.95412.6384
#Mann= 3 , 0 , 0
9249.046  0.0451       09249.046  0.0451       010750.95  0.0451       0
#XS Ineff= 2 , 0
       0                               0
Bank Sta=9249.046,10750.95
Exp/Cntr=0.3,0.1

Type RM Length L Ch R = 1 ,6975.068,244.915300,244.915300,244.915300
XS GIS Cut Line= 6
690871.530241714842032.512859907691154.634666855842287.727167503
 691306.02505492 842459.63653489691353.217333304842530.909920324
691405.002852237842640.326608355691748.212040315843232.651084829
#Sta/Elev= 30
9249.058314.4188 9267.98 306.2379293.607302.00319320.227302.77949346.847 313.416
9374.049319.73019419.508321.50679507.168289.02069567.935271.43669723.413258.9613
9857.878253.08719878.325240.54469949.679237.81639983.223214.0555 10004.8213.1225
10015.63213.443410095.02247.697910129.99255.342710199.94263.6073 10293.2 263.519
10386.47 286.89310416.42291.417610483.95311.442210515.11 327.42910537.18330.0244
10560.13341.999310594.56344.535310628.99 351.76610742.31393.481610750.96399.0391
#Mann= 3 , 0 , 0
9249.058    0.04       09249.058    0.04       010750.96    0.04       0
#XS Ineff= 2 , 0
       0                               0
Bank Sta=9249.058,10750.96
Exp/Cntr=0.3,0.1

Type RM Length L Ch R = 1 ,6730.153,244.915200,244.915200,244.915200
XS GIS Cut Line= 6
690607.782691371842204.931746817690809.843833988842363.948777486
690946.201853131842478.461715692691191.992686905842716.072325941
691505.779238772843113.119291857691633.606176862843290.535966614
#Sta/Elev= 30
9249.034348.7779 9334.57344.26629475.523346.01339591.247314.67539616.645  304.05
9663.294306.76059723.333 299.5099750.493288.04319777.652284.34189797.356276.9728
  9846.7269.57789869.007 261.6489903.116259.9532 9939.91240.96829968.272218.7478
9982.452213.973310010.68212.742310072.78229.960210093.79 239.97610215.99279.8285
10289.15295.0194 10385.9308.549510466.52 303.92310509.18310.033410534.62317.9532
10564.53332.777510584.43336.145510646.61356.446210683.21372.255110750.97419.5458
#Mann= 3 , 0 , 0
9249.034  0.0795       09249.034  0.0795       010750.97  0.0795       0
#XS Ineff= 2 , 0
       0 9548.06                       0
Bank Sta=9249.034,10750.97
Exp/Cntr=0.3,0.1

Type RM Length L Ch R = 1 ,6485.237,244.915300,244.915300,244.915300
XS GIS Cut Line= 6
690394.826941022842494.069217677691086.900670001842928.598177789
691172.199140572 842988.08791508691375.128092656843165.603649677
691475.494117048 843270.69914262691582.254580925843397.211805762
#Sta/Elev= 30
9249.006336.79799320.734343.01269392.255343.31219416.095338.97269535.021304.0698
9620.166298.72099700.834286.33059818.684275.16429877.534275.47989903.151265.8981
 9924.25249.53349962.055228.02799982.349211.29189993.969210.432810020.67213.0561
10124.31253.477810170.28 265.03410237.68295.957910276.93305.456910343.56328.8899
 10439.2338.672810480.72337.141610536.03359.259310563.68362.302710599.77371.9317
10617.78388.768710657.38414.6843 10708.1455.526710735.13481.334210750.95491.5638
#Mann= 3 , 0 , 0
9249.006    0.12       09249.006    0.12       010750.95    0.12       0
#XS Ineff= 2 , 0
       09654.018                       0
Bank Sta=9249.006,10750.95
Exp/Cntr=0.3,0.1

Type RM Length L Ch R = 1 ,6240.322,244.915200,244.915200,244.915200
XS GIS Cut Line= 6
690443.722280487842887.666757338690701.835688474843017.317375173
  690985.0599237843136.439583128691127.873068185843210.599166418
691321.358524825843343.842280584691515.921658351843526.353241712
#Sta/Elev= 30
9491.671313.81939594.373311.48769638.719294.47329717.543290.40849784.016282.4126
9816.917271.36729849.818273.90939969.004 209.7199979.784206.320910001.33205.8404
10022.95207.704810031.31211.626310055.37232.185510098.92261.621610143.45283.9307
10216.52312.671610276.64319.552710350.89 309.52710368.78313.294210413.16337.2696
10453.39341.720510501.11341.028610554.56347.030310594.41372.178410607.62386.6774
10621.81392.838910665.14421.370410707.09458.119410735.05 491.44410750.93515.2572
#Mann= 3 , 0 , 0
9491.671    0.12       09491.671    0.12       010750.93    0.12       0
#XS Ineff= 2 , 0
       09716.553                       0
Bank Sta=9491.671,10750.93
Exp/Cntr=0.3,0.1

Type RM Length L Ch R = 1 ,5995.407,244.915300,244.915300,244.915300
XS GIS Cut Line= 6
690439.298038721843190.727319464690703.773264352843305.412585457
690922.284927808843356.193475281691062.850770467843414.412980533
691262.613809096843537.946891986 691465.18527155843711.538875258
#Sta/Elev= 30
  9583.4307.3196 9736.46289.19789776.623279.8008 9798.36267.85229841.095267.7381
9883.574249.19039956.173202.81379996.779 199.397 10006.9199.750810057.92218.2779
10068.27218.928210099.42235.119110163.35255.567610207.14276.676110229.14278.3613
10250.04290.064810273.84296.716210319.55315.466610354.34339.381710444.43343.5213
10486.95342.552910512.34352.543210550.42356.898910575.82373.261510623.12415.3786
10668.05466.0543 10682.7 477.82710697.35493.677610736.96  519.9910750.89534.5581
#Mann= 3 , 0 , 0
  9583.4  0.1064       0  9583.4  0.1064       010750.89  0.1064       0
#XS Ineff= 2 , 0
       09715.753                       0
Bank Sta=9583.4,10750.89
Exp/Cntr=0.3,0.1

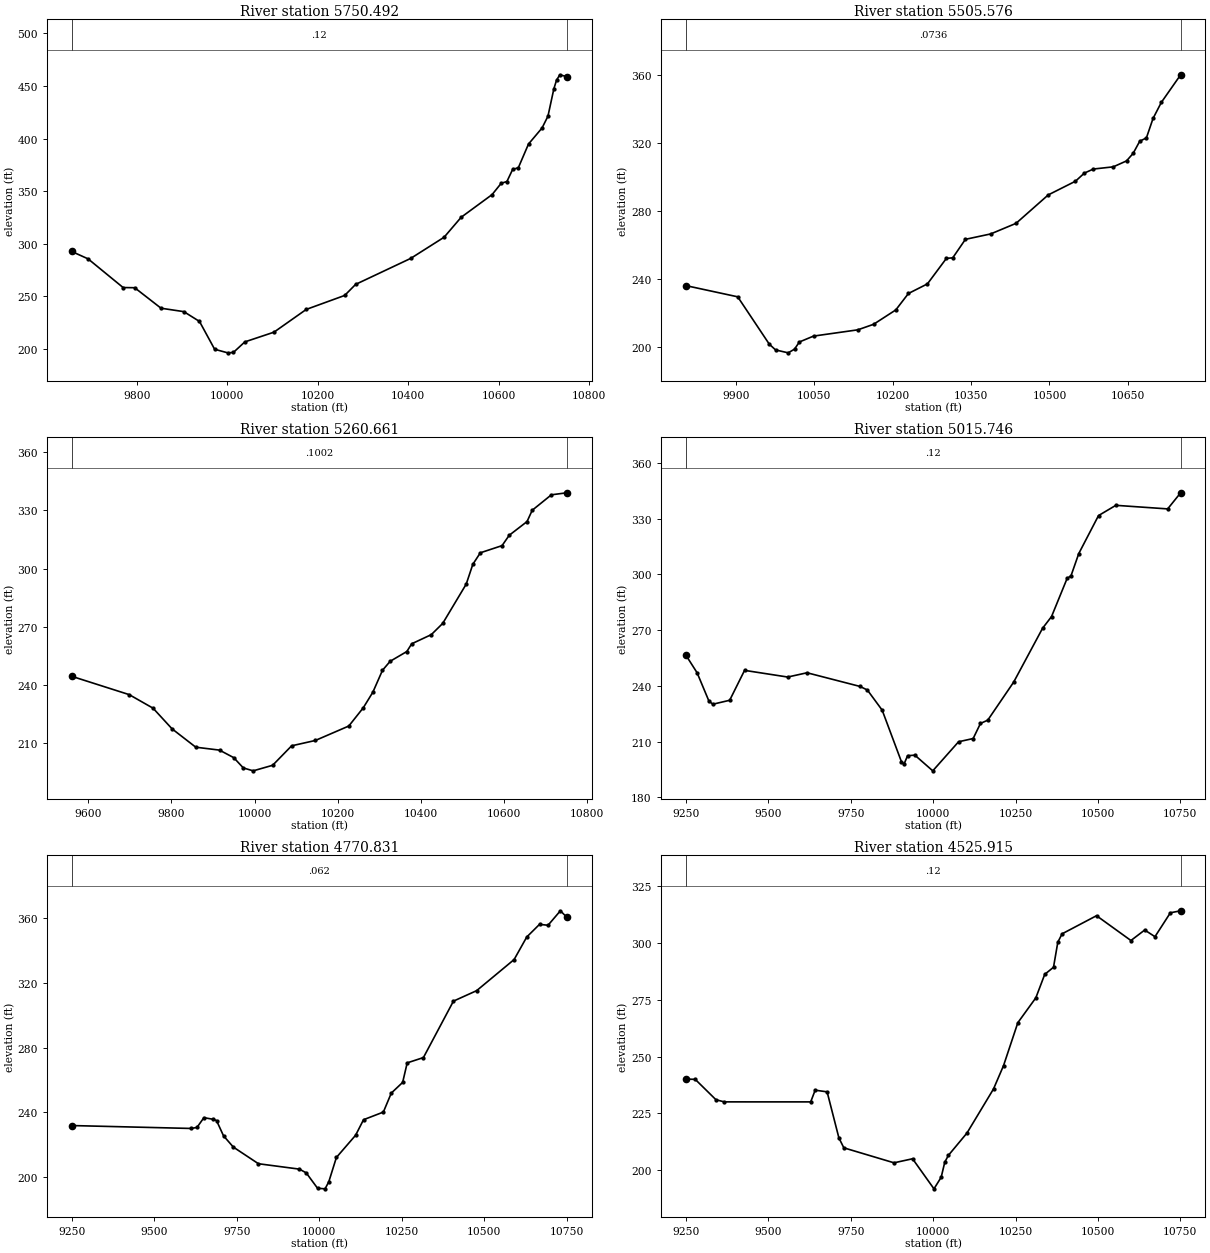
Type RM Length L Ch R = 1 ,5750.492,244.915200,244.915200,244.915200
XS GIS Cut Line= 6
690433.318738223843370.279987738690639.191954292843489.200355898
690817.192384921 843622.99354336691118.678733703843832.830416642
691245.133340821843930.610809192691326.963831802843999.800754284
#Sta/Elev= 30
9656.068292.56689692.145285.56939769.647258.26299795.229258.09119853.498238.5921
9903.939235.33159938.576226.0039 9972.04199.5358   10001196.135510013.37196.4693
10038.85206.551810103.19 215.78910174.64237.438310259.58250.740910283.85261.2747
10405.72286.010910479.44306.123210517.23325.140410585.59346.699610605.72357.4537
10618.36359.1525   10631370.612910643.64372.286810666.09394.800810696.01410.0515
10709.11421.302310722.21447.478610728.04455.4777 10735.3460.701110750.97458.8939
#Mann= 3 , 0 , 0
9656.068    0.12       09656.068    0.12       010750.97    0.12       0
#XS Ineff= 2 , 0
       0 9738.16                       0
Bank Sta=9656.068,10750.97
Exp/Cntr=0.3,0.1

Type RM Length L Ch R = 1 ,5505.576,244.915300,244.915300,244.915300
XS GIS Cut Line= 6
690421.064758386843644.769136193690497.226091487843693.604347828
690585.584292145843753.386648464690948.190459562844000.727163676
691064.717013438844084.841128721691196.663868959 844187.74872747
#Sta/Elev= 30
9803.844236.19769903.706229.55029964.088201.65879976.164198.2465 10000.3196.5376
 10012.4198.726510021.61202.928610048.71206.400210133.45210.097710163.58213.3524
10206.08221.825910230.29 231.518 10266.6237.171610302.92252.218510315.02 252.521
10339.23263.418810387.65266.612610436.07272.839210497.66289.592610549.75297.6654
10566.83302.4588   10584304.845110622.05306.135610647.41 309.63310660.09 314.083
10672.78 321.27410685.46323.183410698.14334.645310713.99 344.10610750.98  360.39
#Mann= 3 , 0 , 0
9803.844  0.0736       09803.844  0.0736       010750.98  0.0736       0
#XS Ineff= 2 , 0
       0                               0
Bank Sta=9803.844,10750.98
Exp/Cntr=0.3,0.1

Type RM Length L Ch R = 1 ,5260.661,244.915200,244.915200,244.915200
XS GIS Cut Line= 6
690055.104018752843729.641398589 690403.03206556843924.480224983
690448.264497332843953.579993885690720.981532188844107.656462062
690910.958273771844230.084943111691071.544494618844347.496390409
#Sta/Elev= 30
9560.098244.38549698.296234.93039755.726227.92059801.372217.26679858.429207.7916
9915.485206.28729949.719202.39619972.772197.0898 9996.51195.590110043.26198.4577
10088.94208.505110146.04211.272110226.44218.721710261.17228.108910284.33236.1926
10307.48247.504810325.98252.147810366.02257.178410377.79 261.17510424.88265.8951
10452.32271.698310508.87291.983710524.71302.181810542.81308.141910595.04311.8431
10612.31317.190410655.09324.252610667.56 330.08710713.64338.070110750.96339.1204
#Mann= 3 , 0 , 0
9560.098  0.1002       09560.098  0.1002       010750.96  0.1002       0
#XS Ineff= 2 , 0
       09597.612                       0
Bank Sta=9560.098,10750.96
Exp/Cntr=0.3,0.1

Type RM Length L Ch R = 1 ,5015.746,244.915300,244.915300,244.915300
XS GIS Cut Line= 6
689705.697556082843800.860206109690108.952972767844056.046932156
690523.033354162844254.883864691690671.366853044 844336.33525176
690844.433117907 844449.05867134690996.188566355844562.286869757
#Sta/Elev= 30
9249.025256.81879284.203247.01429320.219231.71239332.224230.09669383.019232.2074
9428.163248.31069559.004244.71679617.681247.01499778.129239.66719800.608237.7436
9845.557 226.8939903.952199.15769911.692197.77919922.715202.3837 9944.76202.6546
9999.047194.219310077.32209.872710121.57211.6142 10143.7 219.72610165.83221.5055
10244.46 241.99110332.25271.016310359.32277.269210406.56297.804510418.36299.2255
10441.98 311.22110501.82331.637610554.39337.156910711.55335.234110750.97343.9128
#Mann= 3 , 0 , 0
9249.025    0.12       09249.025    0.12       010750.97    0.12       0
#XS Ineff= 2 , 0
       0                               0
Bank Sta=9249.025,10750.97
Exp/Cntr=0.3,0.1

Type RM Length L Ch R = 1 ,4770.831,244.915200,244.915200,244.915200
XS GIS Cut Line= 6
689656.157570402843955.095241845690139.903404782844326.710256327
 690357.15854993844457.065880886690480.536015871 844539.60823905
690678.443491531844684.785100021690869.312807574844837.447138577
#Sta/Elev= 30
9249.052 231.8969611.703230.0966 9628.91230.72849649.971236.77219677.232235.8029
9688.239234.98389709.447225.54629739.263 218.5629815.408208.27649939.675204.9332
9960.306202.63149994.676193.101610017.47 192.74410028.86197.1699 10051.8212.1471
10110.12225.912210134.11235.501610194.26240.233110218.33251.9598 10252.8258.5971
10266.58270.672110315.81273.957210406.83308.863210477.25315.351810590.93334.6029
10629.27348.550210667.98356.370810693.79355.802510731.27364.763910750.97360.7016
#Mann= 3 , 0 , 0
9249.052   0.062       09249.052   0.062       010750.97   0.062       0
#XS Ineff= 2 , 0
       0                               0
Bank Sta=9249.052,10750.97
Exp/Cntr=0.3,0.1

Type RM Length L Ch R = 1 ,4525.915,244.915300,244.915300,244.915300
XS GIS Cut Line= 6
689571.550657881844009.362456342689949.856632732844338.799473843
690030.647686731844455.575878471690119.723228959844647.941831078
690193.085572233 844742.60174592 690590.61463721845085.038236473
#Sta/Elev= 30
9249.092240.16679278.604240.01659341.533231.03579366.705230.10349628.818230.0966
9642.379235.25739678.597234.5194 9714.33214.2431 9729.36209.86559881.516203.2752
9937.737205.057310002.72191.814710024.57196.920510035.42203.518410046.28 206.527
10102.75216.3746 10183.3235.795810213.74246.085310257.07264.968210311.69275.9245
10338.64286.241410365.26289.375410378.31300.405510391.35304.102410495.72312.0754
10600.09301.149710641.86305.7722   10673302.833910719.72313.359910750.92 314.245
#Mann= 3 , 0 , 0
9249.092    0.12       09249.092    0.12       010750.92    0.12       0
#XS Ineff= 2 , 0
       0                               0
Bank Sta=9249.092,10750.92
Exp/Cntr=0.3,0.1

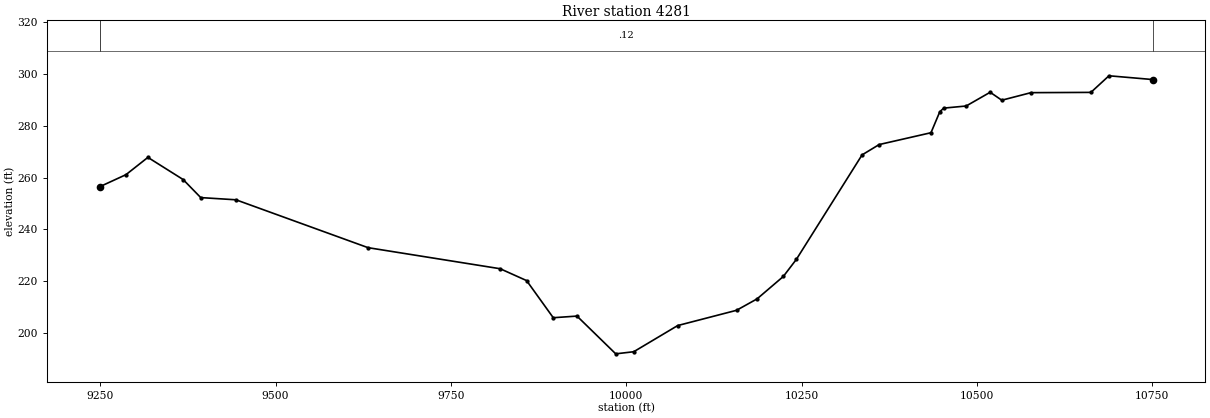
Type RM Length L Ch R = 1 ,    4281,0.000000,0.000000,0.000000
XS GIS Cut Line= 6
689260.196596038844202.263754289689904.207085577 844695.67463285
690089.999475645844815.761699764690192.338314088844886.939898903
690328.726613195844990.108681643690463.424994907845099.770518374
#Sta/Elev= 30
9249.009256.44859286.586261.13059317.843267.80399368.083259.24569393.203252.2667
9443.444251.41659631.845232.91569820.246224.77579857.926220.19219895.955205.8438
 9929.79206.4778 9985.05191.887110010.74192.701910073.43202.817710157.35208.7126
10186.61213.123210224.03221.779910242.74228.4204 10336.4268.773910360.76272.7629
10434.66277.3366 10447.2285.422610452.76286.844510484.81287.660710519.06 292.974
10535.64289.898210577.26292.820110662.72292.923710688.51299.343310750.95297.8866
#Mann= 3 , 0 , 0
9249.009    0.12       09249.009    0.12       010750.95    0.12       0
#XS Ineff= 2 , 0
       0                               0
Bank Sta=9249.009,10750.95
Exp/Cntr=0.3,0.1